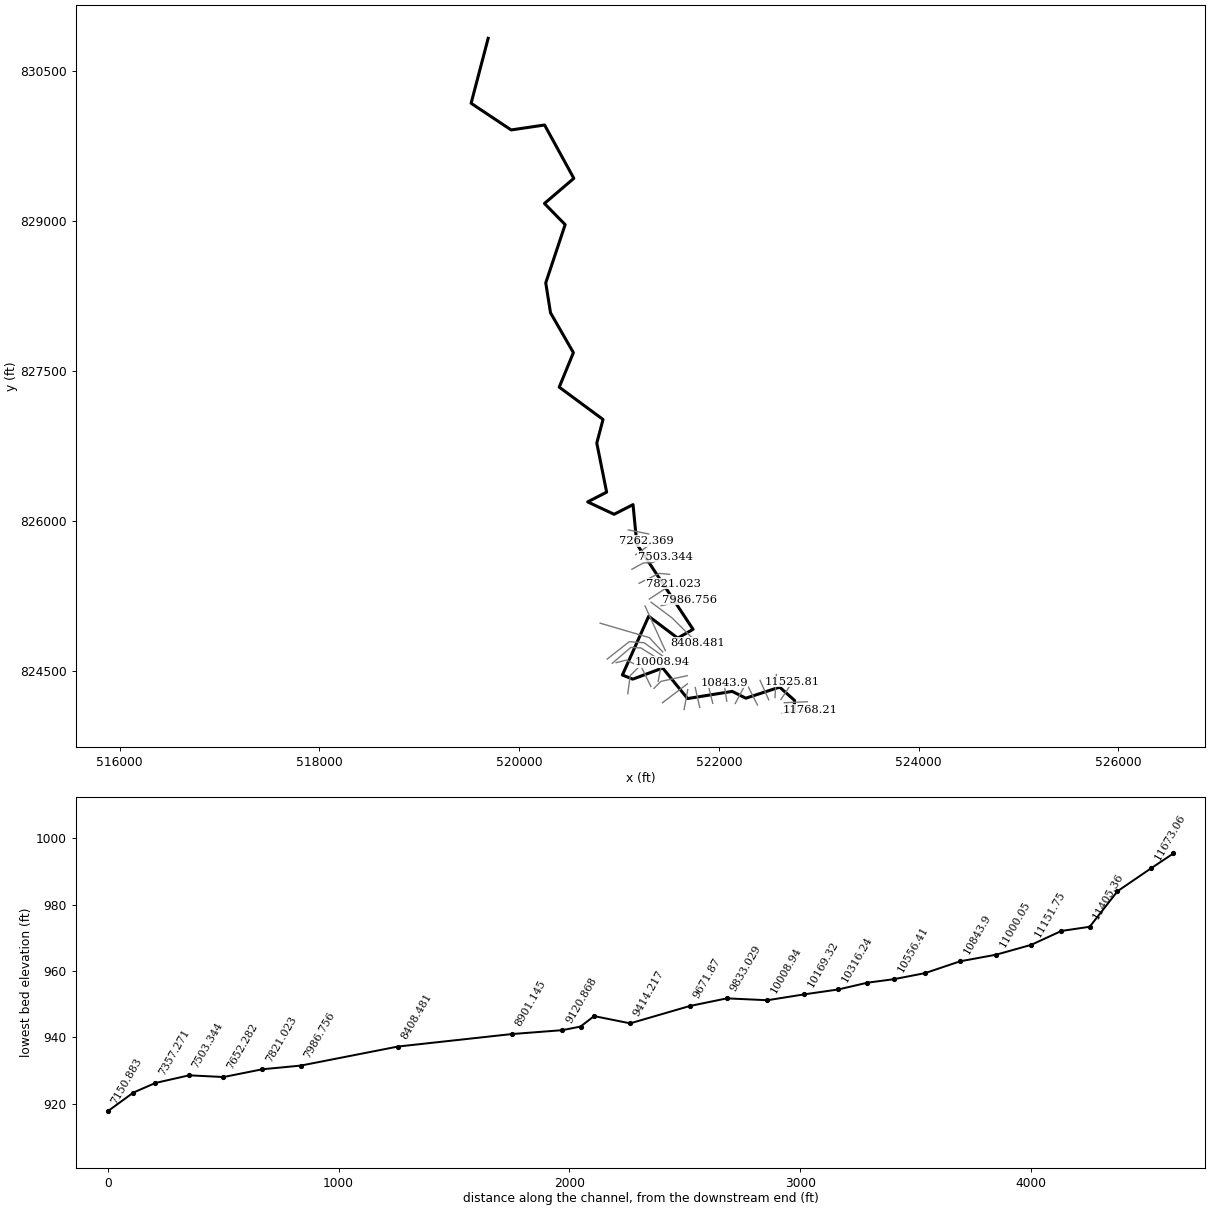
--- 7919_ras.prj (project) ---

Proj Title=7919
Current Plan=p01
Default Exp/Contr=0.3,0.1
English Units
Geom File=g01
Flow File=f01
Plan File=p01
Y Axis Title=Elevation
X Axis Title(PF)=Main Channel Distance
X Axis Title(XS)=Station
BEGIN DESCRIPTION:
RFD model 7919 exported to HEC-RAS
END DESCRIPTION:

--- 7919_ras.p01 (plan) ---

Plan Title=Plan 01
Program Version=4.10
Short Identifier=Plan 01
Geom File=g01
Flow File=f01
Subcritical Flow
Calc Critical at every XS
Secant Critical Depth

--- 7919_ras.f01 (steady flow) ---

Flow Title=Flow 01
Program Version=5.01
Number of Profiles= 6
Profile Names=10yr,25yr,50yr,100yr,100plus,500yr
River Rch & RM=7919,43,11768.21
 4063.99 6242.72 8228.93 9907.6214465.1215249.45
River Rch & RM=7919,43,11525.81
 4066.68 6246.96 8234.62 9914.5714475.2715258.98
River Rch & RM=7919,43,11405.36
    4077 6263.23 8256.43 9941.1814514.1315295.36
River Rch & RM=7919,43,11282.67
  4078.7  6265.9 8260.03 9945.5914520.5615301.42
River Rch & RM=7919,43,11151.75
  4082.8 6272.41 8268.77 9956.2914536.1815316.13
River Rch & RM=7919,43,11000.05
 4084.01 6274.31 8271.34 9959.4314540.7715320.45
River Rch & RM=7919,43, 10843.9
 4085.22 6276.23 8273.91 9962.5814545.3715324.78
River Rch & RM=7919,43,10691.86
 4087.88 6280.44 8279.57  9969.514555.4815334.29
River Rch & RM=7919,43,10556.41
 4090.05 6283.87 8284.18 9975.1614563.7315342.08
River Rch & RM=7919,43,10441.67
 4091.25 6285.78 8286.75  9978.314568.32 15346.4
River Rch & RM=7919,43,10316.24
 4092.21  6287.3  8288.8 9980.8114571.9915349.86
River Rch & RM=7919,43,10169.32
 4092.94 6288.45 8290.35  9982.714574.7515352.45
River Rch & RM=7919,43,10008.94
  4094.4 6290.76 8293.44 9986.4914580.2715357.64
River Rch & RM=7919,43,9833.029
 4228.14 6501.88 8576.8910332.9215086.0615831.02
River Rch & RM=7919,43, 9671.87
 4229.32 6503.76 8579.4210336.03 15090.615835.29
River Rch & RM=7919,43,9414.217
 4239.01 6519.15 8600.1710361.4815127.7615870.29
River Rch & RM=7919,43,9258.191
 4243.98 6527.05 8610.8110374.5315146.81 15888.2
River Rch & RM=7919,43,9120.868
 4245.64 6529.69 8614.3610378.8815153.1715894.17
River Rch & RM=7919,43,8901.145
 4248.74 6534.59 8620.9710386.9715164.9715905.25
River Rch & RM=7919,43,8408.481
 4253.32 6541.83 8630.6910398.8615182.3315921.45
River Rch & RM=7919,43,7986.756
 4285.44 6592.42 8698.5110481.65 15303.216033.78
River Rch & RM=7919,43,7821.023
 4329.91 6662.24 8791.9310595.4815469.39 16187.3
River Rch & RM=7919,43,7652.282
 4332.99 6667.13 8798.5110603.5315481.1616198.31
River Rch & RM=7919,43,7503.344
 4336.09 6672.03 8805.1110611.6115492.9516209.31
River Rch & RM=7919,43,7357.271
 4338.69 6676.16 8810.6610618.4215502.8916218.62
River Rch & RM=7919,43,7262.369
 4341.34 6680.33 8816.2710625.27 15512.916227.92
River Rch & RM=7919,43,7150.883
 4343.01 6682.98 8819.8210629.6215519.2416233.84
River Rch & RM=7919,43,7024.866
 4343.98  6684.5 8821.8710632.1115522.8916237.22
River Rch & RM=7919,43,6857.561
 4368.92 6723.69 8874.3310696.0615616.2416323.38
River Rch & RM=7919,43, 6558.55
 4371.57 6727.86 8879.93 10702.915626.2316332.67
River Rch & RM=7919,43,6351.738
 4372.05 6728.62 8880.9510704.1415628.0516334.35
River Rch & RM=7919,43,6020.254
 4378.51 6738.84 8894.6710720.9215652.5516357.13
River Rch & RM=7919,43,5838.262
 4382.11 6744.52  8902.310730.2515666.1716369.77
River Rch & RM=7919,43,5712.108
 4387.94 6753.69 8914.5810745.2315688.04   16390
River Rch & RM=7919,43,5153.964
 4797.48 7390.61 9761.7411771.8317186.8817742.55
Boundary for River Rch & Prof#=7919,43,1
Up Type= 0
Dn Type= 2
Boundary for River Rch & Prof#=7919,43,2
Up Type= 0
Dn Type= 2
Boundary for River Rch & Prof#=7919,43,2
Up Type= 0
Dn Type= 2
Boundary for River Rch & Prof#=7919,43,2
Up Type= 0
Dn Type= 2
Boundary for River Rch & Prof#=7919,43,2
Up Type= 0
Dn Type= 2
Boundary for River Rch & Prof#=7919,43,2
Up Type= 0
Dn Type= 2

--- 7919_ras.g01 (geometry) ---

Geom Title=7919
Program Version=4.10

River Reach=7919,43
Reach XY= 30
522751.005052447824087.778424382522757.396111459824202.057938263
522607.396111459824335.391271591522269.375278145824224.453771591
522132.396111459824292.682938263521685.521111459824220.807938263
521436.562778145824526.537104949521136.562778145824415.078771591
521032.916944891824456.224604949521296.458611548825044.245438278
521587.083611459824825.495438278521740.729444802824913.516271606
521177.969028234825764.818354934521139.590121895826161.114651233
520949.919983089  826064.3264568520685.163038641826188.458401248
520875.267205298826285.680623457520776.742899656826776.566040128
520839.087288767827012.917871147520400.632427663827336.442176729
520542.559511006827681.494260043520313.392844409828079.931760058
520265.649788767828379.410926715520459.877219319828962.093218371
520252.628955454829173.681760058520546.899788827829424.983843371
520253.931038767829958.838010058 519919.29562211829909.358843386
519518.253955454830176.285926729519688.977407396830825.799453959

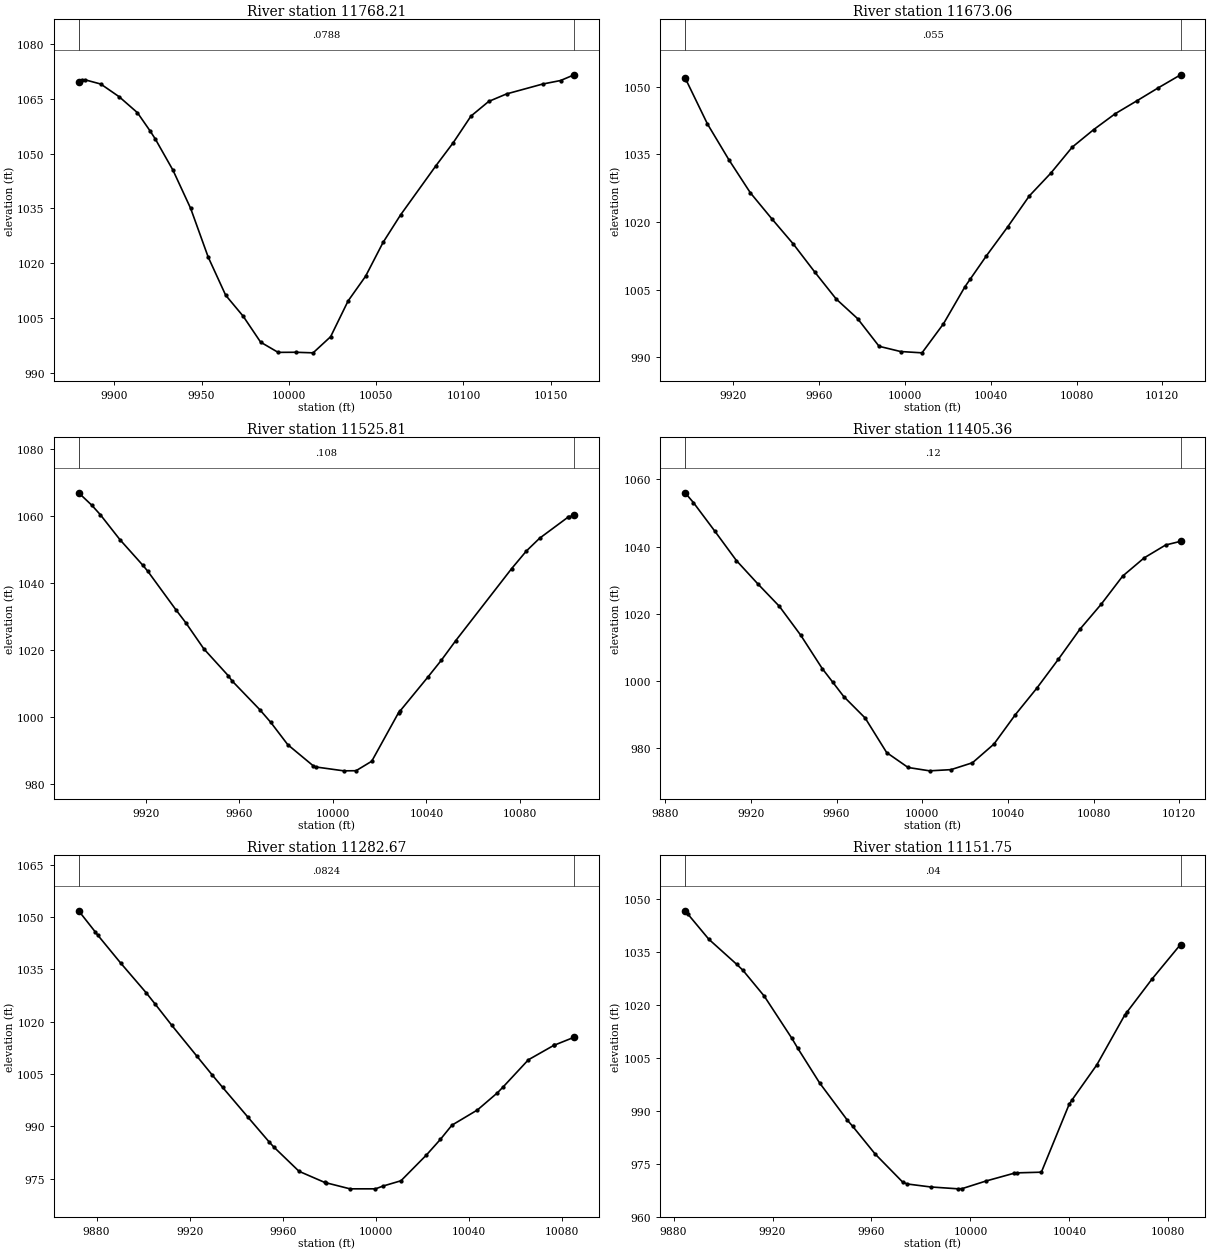
Type RM Length L Ch R = 1 ,11768.21,95.150100,95.150100,95.150100
XS GIS Cut Line= 6
522633.179784538824072.709460592522663.894643882824083.443918875
522690.927358392824088.601783377522811.011611848824087.528741241
 522871.69853405824096.135333677522912.552656348824106.465709001
#Sta/Elev= 30
9879.6191069.7199881.6411070.112 9883.451070.2039892.272 1069.07 9902.811065.594
9913.309 1061.219920.4861056.2569923.4891054.042 9933.671045.4399943.7891034.976
 9953.821021.6479963.8471011.1859973.8551005.4469983.863998.32849993.872995.5317
 10003.9  995.5610013.92995.402910023.95999.826310033.951009.62210043.961016.381
10053.961025.64210063.98 1033.18 10084.11046.57410094.171052.99210104.331060.281
10114.491064.29810124.711066.35710145.341069.05710155.65 1070.0310163.441071.603
#Mann= 3 , 0 , 0
9879.619  0.0788       09879.619  0.0788       010163.44  0.0788       0
#XS Ineff= 2 , 0
       0                               0
Bank Sta=9879.619,10163.44
Exp/Cntr=0.3,0.1

Type RM Length L Ch R = 1 ,11673.06,147.251100,147.251100,147.251100
XS GIS Cut Line= 2
522654.605705112824179.003263846522885.508482873824189.419930518
#Sta/Elev= 27
9897.4241051.9259897.8191051.5329907.8291041.7289917.8391033.7869927.8491026.465
9937.8591020.7069947.8691015.129 9957.881008.918 9967.891002.931  9977.9 998.574
 9987.91992.4498 9997.92991.293510007.93 991.00110017.94997.440310027.951005.645
10030.491007.38110037.96 1012.4910047.97 1018.9610057.981025.76810067.991030.803
   100781036.57410088.011040.46210098.02 1043.9710108.031046.80210118.041049.689
10128.05 1052.4610128.561052.605
#Mann= 3 , 0 , 0
9897.424   0.055       09897.424   0.055       010128.56   0.055       0
#XS Ineff= 2 , 0
       0                               0
Bank Sta=9897.424,10128.56
Exp/Cntr=0.3,0.1

Type RM Length L Ch R = 1 ,11525.81,120.449500,120.449500,120.449500
XS GIS Cut Line= 2
522619.883482903824210.253263846522736.202927351824387.336597174
#Sta/Elev= 30
9891.3411066.982 9897.021063.231 9900.661060.4099908.9841053.0099918.8751045.289
9920.949 1043.539932.9131032.0929937.089 1028.279944.8781020.4099955.304 1012.41
9956.8421010.9289968.8061002.2579973.518998.45269980.771991.80919991.733985.4627
9992.735985.1686 10004.7984.012710009.95984.047410016.66986.878410028.161001.406
10028.631001.75110040.59 1011.9310046.38 1016.9810052.561022.85110076.491044.371
 10082.81049.62910088.45 1053.4310100.411059.61110101.021059.81710103.211060.271
#Mann= 3 , 0 , 0
9891.341   0.108       09891.341   0.108       010103.21   0.108       0
#XS Ineff= 2 , 0
       0                               0
Bank Sta=9891.341,10103.21
Exp/Cntr=0.3,0.1

Type RM Length L Ch R = 1 ,11405.36,122.692500,122.692500,122.692500
XS GIS Cut Line= 2
522560.855705112824231.086597174522574.744593978824461.989374965
#Sta/Elev= 26
9889.3041056.0439893.2251053.1029903.2431044.5719913.2611035.8689923.2791028.922
9933.2971022.2649943.3151013.6279953.333 1003.729958.328999.59859963.351995.4134
9973.369989.00759983.388978.73859993.406 974.29810003.42973.300810013.44973.6582
10023.46975.709410033.48981.2706 10043.5990.042410053.51997.917810063.53 1006.49
10073.551015.39510083.571022.90610093.591031.271 10103.61036.67310113.621040.505
10120.621041.602
#Mann= 3 , 0 , 0
9889.304    0.12       09889.304    0.12       010120.62    0.12       0
#XS Ineff= 2 , 0
       0                               0
Bank Sta=9889.304,10120.62
Exp/Cntr=0.3,0.1

Type RM Length L Ch R = 1 ,11282.67,130.921100,130.921100,130.921100
XS GIS Cut Line= 2
522498.355705112824208.517152727 522411.55014953824402.961597174
#Sta/Elev= 30
9872.3141051.8249879.4141045.8039880.5461044.8229890.3651036.8399901.3161028.322
9905.0771025.1599912.2671019.0269923.2191010.0369929.6071004.803 9934.171001.168
9945.121992.56429954.138985.53299956.072984.11589967.024977.06899977.975973.9004
9978.669973.77259988.926972.03839999.877972.0401 10003.2972.850910010.83974.3571
10021.78981.753410027.73 986.19610032.73990.305810043.68994.667510052.26999.5826
10054.631001.20410065.581009.06610076.541013.21910076.791013.27910085.261015.542
#Mann= 3 , 0 , 0
9872.314  0.0824       09872.314  0.0824       010085.26  0.0824       0
#XS Ineff= 2 , 0
       0                               0
Bank Sta=9872.314,10085.26
Exp/Cntr=0.3,0.1

Type RM Length L Ch R = 1 ,11151.75,151.696900,151.696900,151.696900
XS GIS Cut Line= 2
522385.508482903824156.433819428522295.230705082824335.253263846
#Sta/Elev= 29
 9884.661046.7069885.7881045.7649894.2561038.6319905.4581031.5629907.9771029.878
 9916.661022.4999927.8621010.4889930.1661007.7589939.064997.85579950.266987.3018
9952.354985.62519961.468977.7395 9972.67969.72359974.543969.21859983.873968.3836
9995.075967.84739996.732967.928110006.28 970.06310017.48972.240210018.92972.3804
10028.68972.571110039.88 991.77110041.11993.099710051.091002.99710062.291017.017
 10063.31017.98510073.49 1027.4210084.691036.93510084.981037.085
#Mann= 3 , 0 , 0
 9884.66    0.04       0 9884.66    0.04       010084.98    0.04       0
#XS Ineff= 2 , 0
       0                               0
Bank Sta=9884.66,10084.98
Exp/Cntr=0.3,0.1

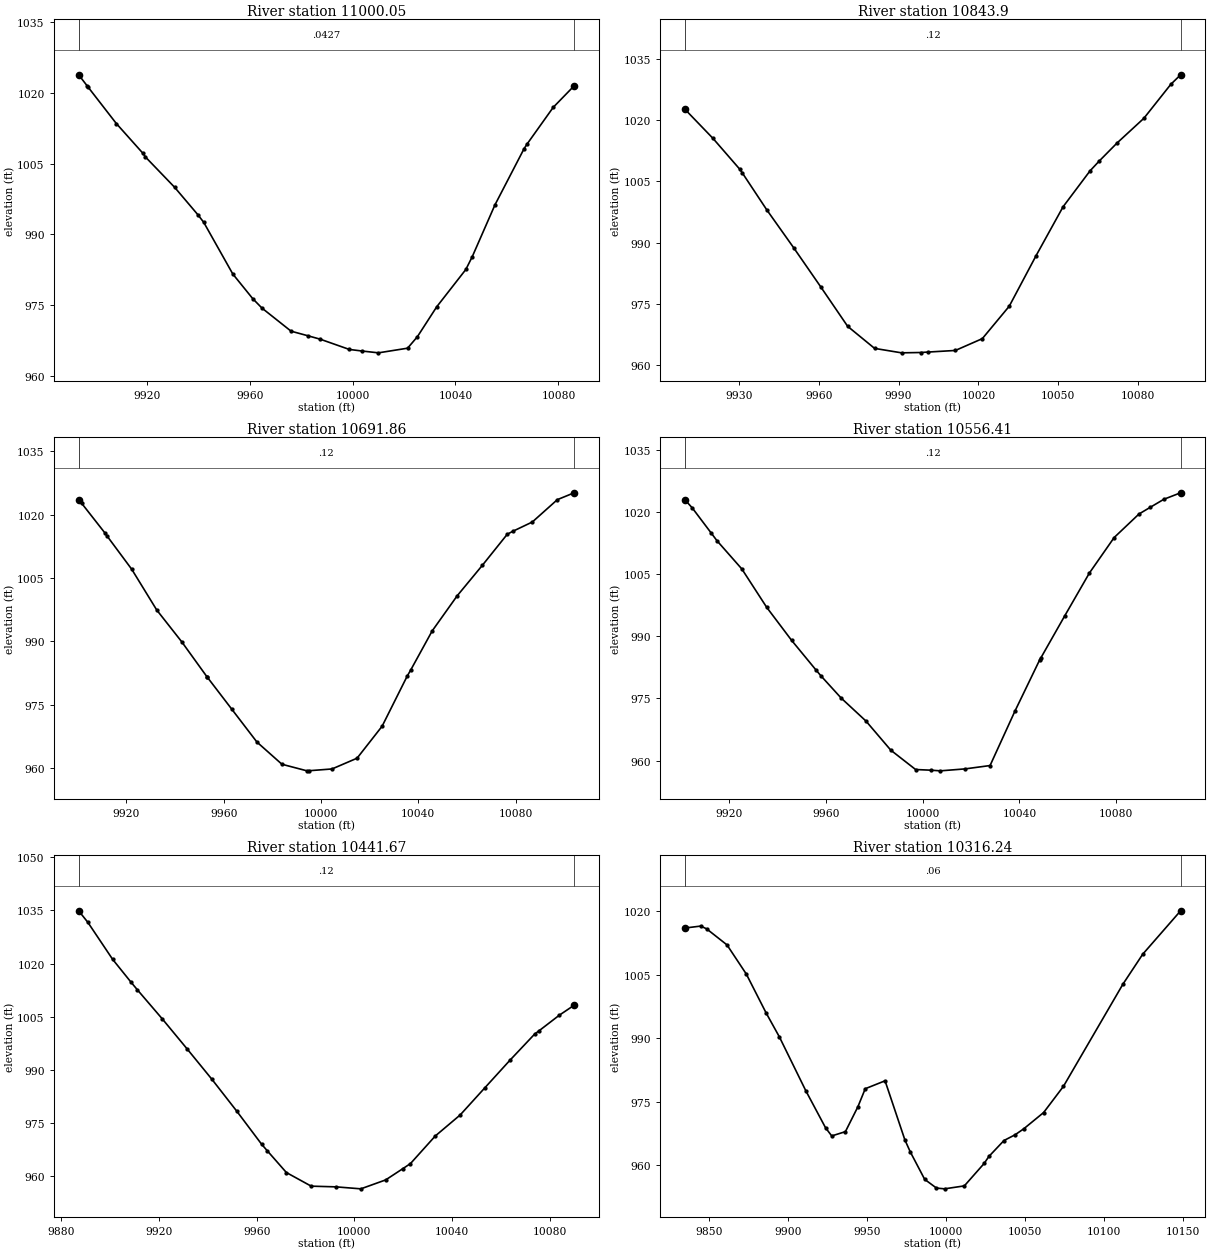
Type RM Length L Ch R = 1 ,11000.05,156.151900,156.151900,156.151900
XS GIS Cut Line= 2
522163.286260635824172.058819428522253.564038455824342.197708294
#Sta/Elev= 28
9893.5211023.7999896.8511021.4399897.1781021.2019908.1711013.4749918.5121007.162
9919.4921006.3839930.813999.97269939.847994.16269942.133992.54929953.454981.5854
9961.182976.37829964.774974.37419976.095969.47829982.517968.52529987.415967.7836
9998.736965.611310003.85 965.26510010.06964.890910021.38965.876610025.19968.3057
 10032.7 974.64210044.02982.550310046.52985.264710055.34996.238910066.661008.142
10067.861009.15110077.981016.89410086.131021.462
#Mann= 3 , 0 , 0
9893.521  0.0427       09893.521  0.0427       010086.13  0.0427       0
#XS Ineff= 2 , 0
       0                               0
Bank Sta=9893.521,10086.13
Exp/Cntr=0.3,0.1

Type RM Length L Ch R = 1 , 10843.9,152.038600,152.038600,152.038600
XS GIS Cut Line= 2
522078.216816217824194.628263846522050.439038426824378.656041622
#Sta/Elev= 24
9909.8411022.7189910.2171022.432 9920.331015.5669930.443 1007.959931.3941007.034
9940.557997.9852 9950.67988.66419960.783979.10429970.896969.4067 9981.01963.9888
9991.123962.89619998.394962.978610001.24963.093510011.35963.481510021.46966.3822
10031.58974.349410041.69986.8084 10051.8998.781110061.92  1007.610065.391010.026
10072.03 1014.4210082.141020.51310092.261028.85810095.951031.205
#Mann= 3 , 0 , 0
9909.841    0.12       09909.841    0.12       010095.95    0.12       0
#XS Ineff= 2 , 0
       0                               0
Bank Sta=9909.841,10095.95
Exp/Cntr=0.3,0.1

Type RM Length L Ch R = 1 ,10691.86,135.453300,135.453300,135.453300
XS GIS Cut Line= 2
521937.591816217824173.794930518521888.980705082824371.711597174
#Sta/Elev= 27
9900.3281023.5429901.5691022.7239911.1941015.6499911.8661015.0889922.1631007.092
 9932.46997.43149942.757989.88689953.055981.65879953.118981.61389963.352973.9127
9973.649966.16069983.946960.89139994.243959.33459995.042 959.35910004.54959.7803
10014.84962.329410025.14969.902110035.43981.744410036.97983.284610045.73992.4792
10056.031000.81510066.321007.98910076.621015.39110078.891016.08410086.921018.286
10097.221023.58510104.13 1025.21
#Mann= 3 , 0 , 0
9900.328    0.12       09900.328    0.12       010104.13    0.12       0
#XS Ineff= 2 , 0
       0                               0
Bank Sta=9900.328,10104.13
Exp/Cntr=0.3,0.1

Type RM Length L Ch R = 1 ,10556.41,114.735100,114.735100,114.735100
XS GIS Cut Line= 2
521807.383482873824132.128263846521762.244593978824331.781041622
#Sta/Elev= 27
9901.9241023.0189904.8681021.1029912.732    1015 9915.121013.1419925.3731006.322
9935.625997.05349945.877989.0936 9956.13981.79529958.079980.45159966.382975.1114
9976.635969.54539986.887962.50569997.139957.821910003.43957.661910007.39957.5038
10017.64 957.978 10027.9958.784810038.15971.9163 10048.4984.345710048.77984.7061
10058.65994.893610068.911005.32910079.161013.93110089.411019.61910094.121021.258
10099.661023.17310106.621024.754
#Mann= 3 , 0 , 0
9901.924    0.12       09901.924    0.12       010106.62    0.12       0
#XS Ineff= 2 , 0
       0                               0
Bank Sta=9901.924,10106.62
Exp/Cntr=0.3,0.1

Type RM Length L Ch R = 1 ,10441.67,125.432400,125.432400,125.432400
XS GIS Cut Line= 2
521651.133482873824111.294930518521687.591816187824310.947708294
#Sta/Elev= 26
9887.0831034.9119890.849 1031.669901.0151021.2049908.6071014.705 9911.181012.578
9921.3461004.4029931.511995.93599941.676987.35379951.842978.37039962.007969.0502
9964.274967.24419972.172 961.0479982.338957.20089992.503957.003710002.67956.4451
10012.83958.961410019.94962.1725   10023 963.57910033.16971.361610043.33977.2785
 10053.5984.989810063.66992.679710073.831000.09810075.611001.02510083.991005.461
10090.041008.264
#Mann= 3 , 0 , 0
9887.083    0.12       09887.083    0.12       010090.04    0.12       0
#XS Ineff= 2 , 0
       0                               0
Bank Sta=9887.083,10090.04
Exp/Cntr=0.3,0.1

Type RM Length L Ch R = 1 ,10316.24,146.915800,146.915800,146.915800
XS GIS Cut Line= 2
521434.119593978824179.003263846521684.119593978824368.239374965
#Sta/Elev= 30
9834.7731015.9899844.7091016.4469848.4191015.7819861.2781012.0029873.5031005.121
9886.045995.93319894.416990.29279911.128977.5879 9923.67968.81169927.554966.9056
9936.212967.91589944.123973.80229948.754978.04919961.295979.91619973.837965.9699
9977.261963.13449986.379956.6484 9993.83954.59699998.921 954.41510011.46955.1113
   10024960.410810026.97962.052310036.55965.825110043.54967.169110049.09968.5962
10061.63972.429310074.17 978.613 10111.8 1002.7310124.341009.80610148.321020.055
#Mann= 3 , 0 , 0
9834.773    0.06       09834.773    0.06       010148.32    0.06       0
#XS Ineff= 2 , 0
       09957.066                       0
Bank Sta=9834.773,10148.32
Exp/Cntr=0.3,0.1

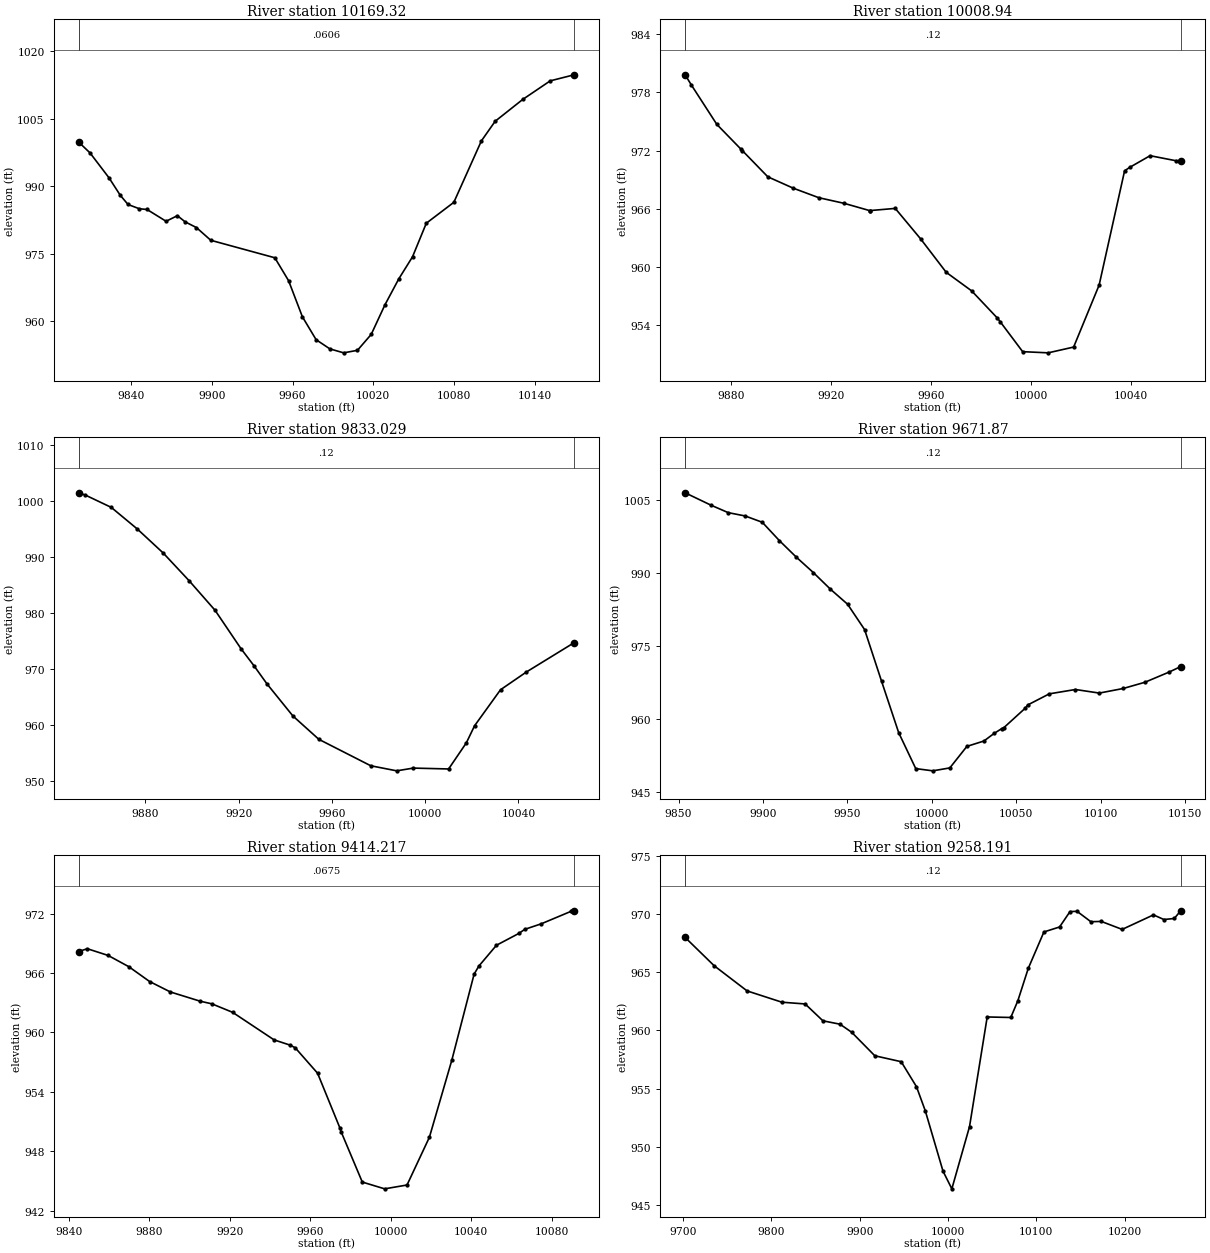
Type RM Length L Ch R = 1 ,10169.32,160.382600,160.382600,160.382600
XS GIS Cut Line= 3
 521349.05014953824323.100486055521418.494593978824392.544930503
521682.383482873824449.836597174
#Sta/Elev= 30
9801.023999.80619809.437997.41169823.579991.86269831.994987.96019837.722 985.927
9846.136984.97789851.864984.81579866.006982.1932 9874.42983.43669880.148982.0713
9888.562980.79549899.232977.96739946.821974.08069957.054968.98099967.287960.9713
 9977.52 955.8639987.753953.82029997.986952.945510008.22953.506710018.45957.0436
10028.68963.637910038.92969.380410049.15974.298610059.38981.757510079.85986.4081
10100.321000.06210110.551004.42710131.011009.27310151.481013.41210169.271014.762
#Mann= 3 , 0 , 0
9801.023  0.0606       09801.023  0.0606       010169.27  0.0606       0
#XS Ineff= 2 , 0
       0                               0
Bank Sta=9801.023,10169.27
Exp/Cntr=0.3,0.1

Type RM Length L Ch R = 1 ,10008.94,175.912700,175.912700,175.912700
XS GIS Cut Line= 2
521390.716816187824392.544930503521428.911260635824586.989374951
#Sta/Elev= 26
9861.714979.79769864.216978.74749874.407974.68879883.936972.16989884.598971.9925
 9894.79969.29329904.981968.12089915.172967.14329925.363966.55869935.554965.8107
9935.818965.82059945.745 966.0419955.936962.89149966.127959.46139976.318957.5469
9986.509954.7703  9987.7954.3804  9996.7951.291810006.89 951.17110017.08951.7648
10027.27958.141810037.46969.912510039.58970.276710047.66971.466610057.85970.9558
10059.87970.9237
#Mann= 3 , 0 , 0
9861.714    0.12       09861.714    0.12       010059.87    0.12       0
#XS Ineff= 2 , 0
       0                               0
Bank Sta=9861.714,10059.87
Exp/Cntr=0.3,0.1

Type RM Length L Ch R = 1 ,9833.029,161.159700,161.159700,161.159700
XS GIS Cut Line= 2
521318.017163455824342.414722174521224.701191187824533.386944413
#Sta/Elev= 21
9851.3841001.4499854.261 1001.049865.391 998.8359876.521994.98329887.651990.6829
9898.781985.72289909.911980.43419921.041973.56399926.589970.52559932.171967.2776
9943.301961.53689954.431957.36369976.691952.63789987.821951.73059994.922952.2218
10010.08952.0652 10017.7956.743110021.21959.783610032.34966.224610043.47969.4101
10063.94974.6507
#Mann= 3 , 0 , 0
9851.384    0.12       09851.384    0.12       010063.94    0.12       0
#XS Ineff= 2 , 0
       0                               0
Bank Sta=9851.384,10063.94
Exp/Cntr=0.3,0.1

Type RM Length L Ch R = 1 , 9671.87,257.652900,257.652900,257.652900
XS GIS Cut Line= 3
521086.897371769824269.715069398521111.853968978824450.921666607
521189.978968978824529.046666607
#Sta/Elev= 30
9853.8531006.4039869.2821003.8469879.3771002.3349889.4711001.6459899.5661000.355
 9909.66996.60539919.754993.19289929.849 990.0299939.943986.62779950.038983.5686
9960.132978.36289970.226967.72579980.321957.23349990.415 949.87110000.51949.4121
 10010.6950.0115 10020.7954.423710030.79955.526410036.77957.069510041.22958.0419
10042.54 958.24710055.36962.288210056.68962.9066 10069.5965.192810084.96966.0827
10099.11965.349510113.25966.289410126.07967.561310140.21969.621610147.26970.7689
#Mann= 3 , 0 , 0
9853.853    0.12       09853.853    0.12       010147.26    0.12       0
#XS Ineff= 2 , 0
       0                               0
Bank Sta=9853.853,10147.26
Exp/Cntr=0.3,0.1

Type RM Length L Ch R = 1 ,9414.217,156.026000,156.026000,156.026000
XS GIS Cut Line= 3
520970.794941187824580.044930503521072.791468978824606.086597204
521199.744593978824544.237638831
#Sta/Elev= 28
9844.773968.17239849.113968.45459859.434967.77669869.755 966.6389880.075965.1438
9890.396964.08879905.226 963.1559911.038962.88979921.359962.0322    9942959.2482
9950.042958.71369952.498958.45279963.622955.88339974.745 950.3479975.355949.9616
9985.869944.88889996.993944.204810008.12944.591610019.24949.410110030.36957.1693
10041.49965.889810043.85966.704910052.61 968.80610063.73969.998110066.69970.4126
10074.86970.969310089.52972.215710091.26972.2872
#Mann= 3 , 0 , 0
9844.773  0.0675       09844.773  0.0675       010091.26  0.0675       0
#XS Ineff= 2 , 0
       0                               0
Bank Sta=9844.773,10091.26
Exp/Cntr=0.3,0.1

Type RM Length L Ch R = 1 ,9258.191,59.000700,59.000700,59.000700
XS GIS Cut Line= 4
520931.602232873824573.577916607521117.713343978824732.605694398
521219.102232873824727.050138846521401.046677321824612.466805518
#Sta/Elev= 30
9702.158968.00129735.134965.56099772.394   963.49811.855962.42929838.162962.2795
9858.283960.83029877.622960.53999890.775959.85189917.082957.82479946.958957.3155
9964.271 955.1679974.286953.08769994.316947.910410004.33946.386710024.36 951.732
10044.39961.161110071.11961.1161 10079.1962.554210090.92965.340710108.64968.4685
10126.38968.896410138.19970.219710146.17970.241810161.83969.348510173.65969.3733
10197.28968.688410232.74969.936110244.55969.537210256.37969.626910263.52970.2887
#Mann= 3 , 0 , 0
9702.158    0.12       09702.158    0.12       010263.52    0.12       0
#XS Ineff= 2 , 0
       09936.151         10057.8       0
Bank Sta=9702.158,10263.52
Exp/Cntr=0.3,0.1

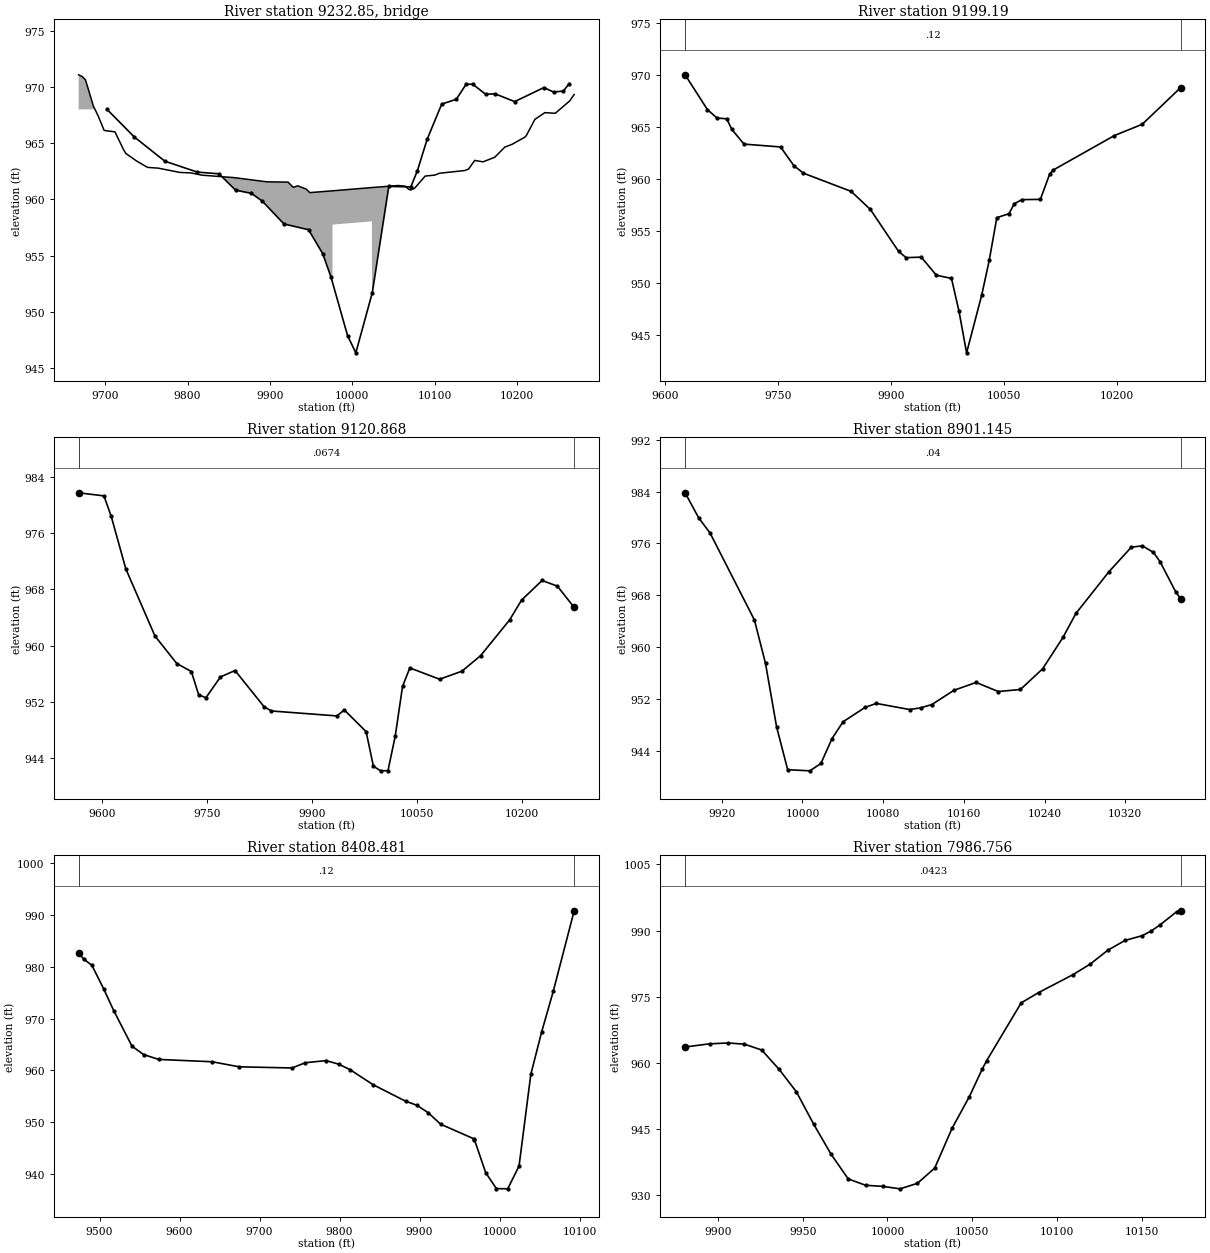
Type RM Length L Ch R = 3 , 9232.85,,,
BEGIN DESCRIPTION:
END DESCRIPTION:
Bridge Culvert--1,0,-1,-1, 0
Deck Dist Width WeirC Skew NumUp NumDn MinLoCord MaxHiCord MaxSubmerge Is_Ogee
17.361250,24.278200,2.6,0, 48, 48, , , 0.95, 0, 0,0,,
 9667.71 9672.36 9676.09 9685.53 9691.46 9698.69 9711.86 9722.22 9725.02 9737.59
 9751.35 9764.51 9790.84 9804.01 9817.17 9856.66 9896.16 9922.11 9928.25 9933.89
 9943.93 9948.56 9976.05 9976.0510023.9510023.9510055.8610064.4110068.3910071.01
10075.7410088.5710100.0710106.1210136.5810141.2210148.7510158.7710173.0810185.25
10193.8810209.5910211.4310221.7510233.9210246.5310264.0810269.50
  971.07  970.90  970.61  968.31  967.41  966.13  966.00  964.43  964.09  963.44
  962.85  962.78  962.40  962.36  962.16  961.94  961.57  961.54  961.08  961.21
  960.93  960.61  960.77  960.77  961.06  961.06  961.24  961.18  960.91  960.84
  961.00  962.08  962.16  962.33  962.57  962.70  963.47  963.34  963.75  964.65
  964.89  965.53  965.68  967.11  967.71  967.65  968.75  969.32
  -28.93  -29.10  -29.39  -31.69  -32.59  -33.87  -34.00  -35.57  -35.91  -36.56
  -37.15  -37.22  -37.60  -37.64  -37.84  -38.06  -38.43  -38.46  -38.92  -38.79
  -39.07  -39.39  -39.23  957.77  958.06  -38.94  -38.76  -38.82  -39.09  -39.16
  -39.00  -37.92  -37.84  -37.67  -37.43  -37.30  -36.53  -36.66  -36.25  -35.35
  -35.11  -34.47  -34.32  -32.89  -32.29  -32.35  -31.25  -30.68
 9667.71 9672.36 9676.09 9685.53 9691.46 9698.69 9711.86 9722.22 9725.02 9737.59
 9751.35 9764.51 9790.84 9804.01 9817.17 9856.66 9896.16 9922.11 9928.25 9933.89
 9943.93 9948.56 9976.05 9976.0510023.9510023.9510055.8610064.4110068.3910071.01
10075.7410088.5710100.0710106.1210136.5810141.2210148.7510158.7710173.0810185.25
10193.8810209.5910211.4310221.7510233.9210246.5310264.0810269.50
  971.07  970.90  970.61  968.31  967.41  966.13  966.00  964.43  964.09  963.44
  962.85  962.78  962.40  962.36  962.16  961.94  961.57  961.54  961.08  961.21
  960.93  960.61  960.77  960.77  961.06  961.06  961.24  961.18  960.91  960.84
  961.00  962.08  962.16  962.33  962.57  962.70  963.47  963.34  963.75  964.65
  964.89  965.53  965.68  967.11  967.71  967.65  968.75  969.32
  -28.93  -29.10  -29.39  -31.69  -32.59  -33.87  -34.00  -35.57  -35.91  -36.56
  -37.15  -37.22  -37.60  -37.64  -37.84  -38.06  -38.43  -38.46  -38.92  -38.79
  -39.07  -39.39  -39.23  957.77  958.06  -38.94  -38.76  -38.82  -39.09  -39.16
  -39.00  -37.92  -37.84  -37.67  -37.43  -37.30  -36.53  -36.66  -36.25  -35.35
  -35.11  -34.47  -34.32  -32.89  -32.29  -32.35  -31.25  -30.68
BR Coef=-1 , 0 , 0 ,, 0 ,,,0.8,0,1,0,
WSPro=,,,, 1 ,,,, 0 ,,,, 0 ,,,,-1 ,-1 ,-1 , 0 , 0 , 0 , 0 , 0
BC Design=,, 0 ,, 0 ,,,,,,

Type RM Length L Ch R = 1 , 9199.19,78.322000,78.322000,78.322000
XS GIS Cut Line= 4
520881.602232903824616.633472189521102.435566187824790.244583279
521251.046677321824779.133472189521436.463344008824646.494583279
#Sta/Elev= 30
 9627.11970.00589656.827966.64379669.593965.83889682.313965.77089689.188964.7424
9705.368 963.3319753.908963.05679771.355961.26849784.075960.53749847.677958.7774
9873.117957.03979910.588 952.9989920.615952.40099940.671 952.4519960.727 950.708
9980.783950.40229990.811947.220710000.84943.237210020.89948.788110030.92952.1474
10040.95956.248410057.04956.630810064.15 957.585 10074.2957.985810098.79958.0106
10111.08960.433110115.71  960.8310197.15964.157510234.04965.241910285.02968.7675
#Mann= 3 , 0 , 0
 9627.11    0.12       0 9627.11    0.12       010285.02    0.12       0
#XS Ineff= 2 , 0
       09933.967        10066.07       0
Bank Sta=9627.11,10285.02
Exp/Cntr=0.3,0.1

Type RM Length L Ch R = 1 ,9120.868,219.723100,219.723100,219.723100
XS GIS Cut Line= 3
520810.204663426824975.010208279521302.826191187824830.695972189
521436.289732873824687.466805518
#Sta/Elev= 30
9565.863981.78239602.121981.33719612.541978.40949633.382970.94149675.063961.3703
9706.324957.44799727.164956.30979737.584953.00099748.005952.56569768.845955.5398
9789.686956.44789831.367951.27279841.787 950.684 9935.57949.9781 9945.99950.8323
9977.251947.73959987.671942.80449998.091942.152110008.51942.176310018.93 947.112
10029.35 954.17510039.77956.823710082.38955.208110114.31956.351710141.05 958.566
10182.65963.668610199.73966.491910229.06969.2844   10251968.470510274.96965.4431
#Mann= 3 , 0 , 0
9565.863  0.0674       09565.863  0.0674       010274.96  0.0674       0
#XS Ineff= 2 , 0
       09897.838        10102.16       0
Bank Sta=9565.863,10274.96
Exp/Cntr=0.3,0.1

Type RM Length L Ch R = 1 ,8901.145,492.663700,492.663700,492.663700
XS GIS Cut Line= 2
521259.423413426825147.536249965521463.416468978824700.487638861
#Sta/Elev= 30
9883.601983.80359897.034979.95449908.372977.5972 9952.34964.21279963.332957.5278
9974.324947.75189985.316941.1504 10007.3940.974610018.29942.111110029.28945.9398
10040.28948.534310062.26950.766410073.25951.357110106.23950.418710117.22950.6765
10128.21951.177910150.19953.377610172.18954.590610194.16  953.1910216.15953.5074
10238.13956.688410258.36961.537510271.11965.212210304.08971.677310326.06975.4182
10337.06975.635910348.05974.615510354.72973.155810370.03 968.55910374.99967.4928
#Mann= 3 , 0 , 0
9883.601    0.04       09883.601    0.04       010374.99    0.04       0
#XS Ineff= 2 , 0
       0                               0
Bank Sta=9883.601,10374.99
Exp/Cntr=0.3,0.1

Type RM Length L Ch R = 1 ,8408.481,421.724700,421.724700,421.724700
XS GIS Cut Line= 3
521319.883482903825184.906041607521530.855705112825027.406041607
 521783.42514959824776.442499951
#Sta/Elev= 30
 9473.83982.56979480.215981.45229490.389980.24289505.174975.69859517.653971.5359
9540.538 964.6769555.091963.0632 9573.97962.12799640.834961.67849674.266960.7086
9740.522960.48289757.048961.48579783.085961.9066 9799.34961.18869813.437960.1237
9841.632957.28229882.397954.09659896.584953.30239910.772951.86959926.215949.6625
9967.522946.86799968.507946.67399982.604 940.3269995.896937.269510010.08937.2186
10024.27941.611510038.99959.267210052.65967.495510067.19975.333210093.16990.7413
#Mann= 3 , 0 , 0
 9473.83    0.12       0 9473.83    0.12       010093.16    0.12       0
#XS Ineff= 2 , 0
       0                               0
Bank Sta=9473.83,10093.16
Exp/Cntr=0.3,0.1

Type RM Length L Ch R = 1 ,7986.756,165.733600,165.733600,165.733600
XS GIS Cut Line= 2
521420.699455082825149.888680503521707.157788455825208.482430518
#Sta/Elev= 30
9880.604963.61219895.201964.3358 9906.11964.52069915.615964.24969925.822 962.923
9936.029958.56819946.236953.47969956.443946.1403 9966.65939.36269976.857933.7191
9987.064932.28149997.271932.027410007.48931.471510017.69932.725110027.89936.1761
 10038.1945.173610048.31952.343110055.81958.514510058.51960.497610078.93973.6175
10089.13975.929810109.55980.019710119.76 982.42910129.96985.523910140.17987.7546
10150.38988.840510155.62989.897310160.58991.206110170.79994.306910172.99994.4753
#Mann= 3 , 0 , 0
9880.604  0.0423       09880.604  0.0423       010172.99  0.0423       0
#XS Ineff= 2 , 0
       0                               0
Bank Sta=9880.604,10172.99
Exp/Cntr=0.3,0.1

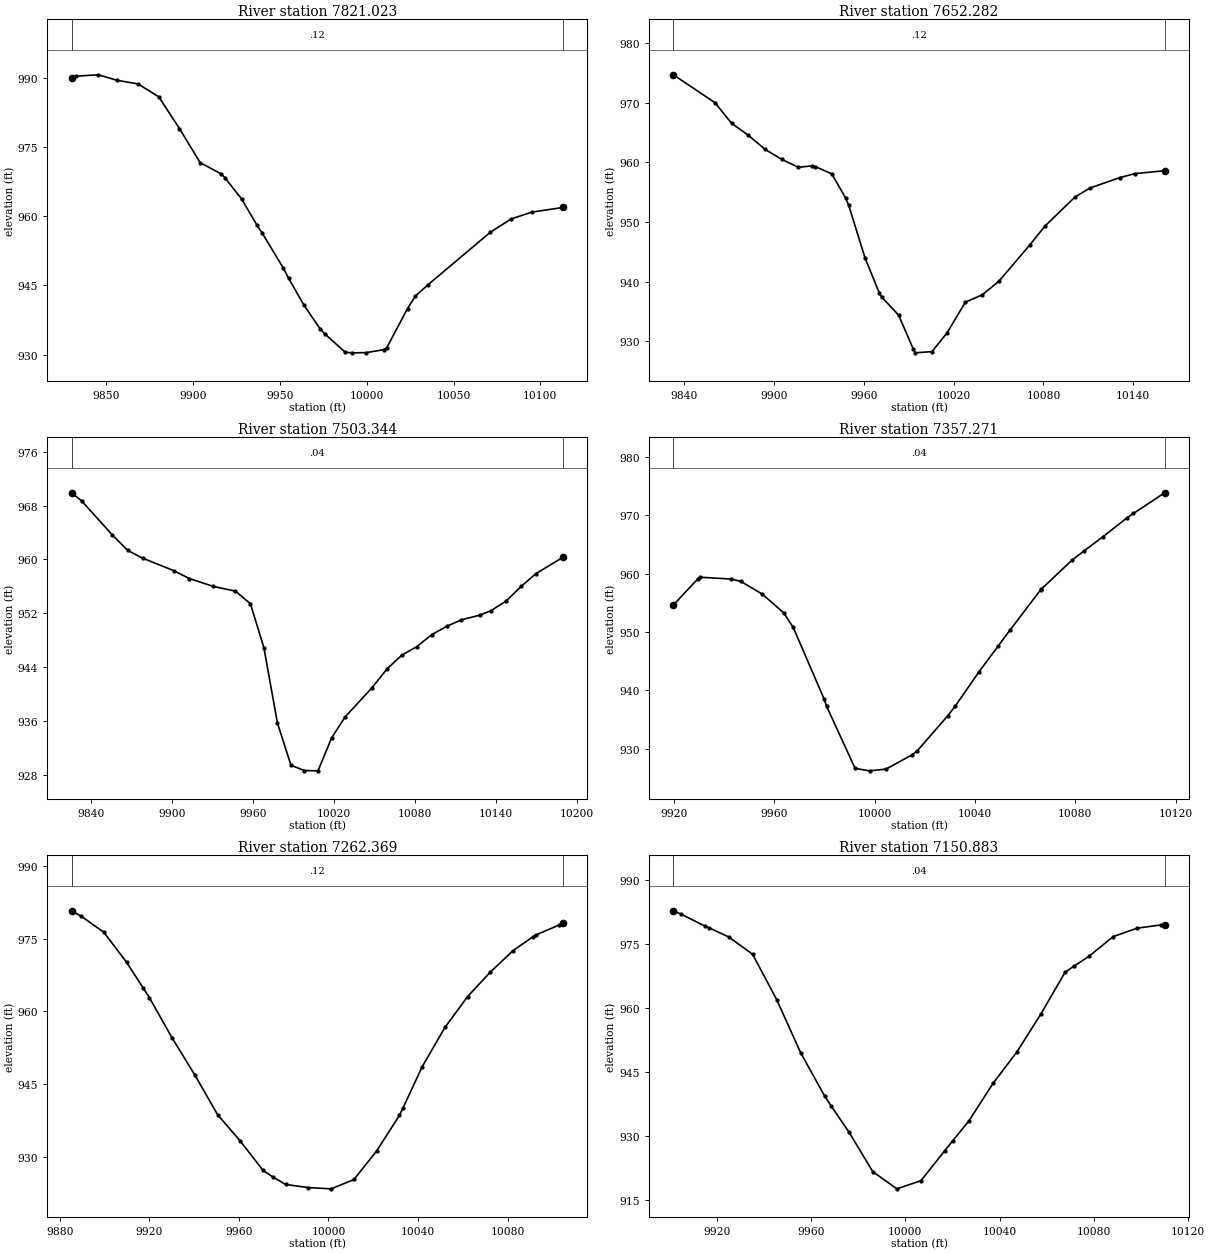
Type RM Length L Ch R = 1 ,7821.023,168.740900,168.740900,168.740900
XS GIS Cut Line= 2
 521302.95639953825216.546666607521539.935566217825371.494583294
#Sta/Elev= 30
9829.873990.00279832.314990.31639845.319990.6214 9856.21989.41319868.158988.6441
9880.106985.85069892.053978.97289904.001971.57349915.949969.17619918.412968.2512
9927.897963.68859936.685958.06199939.845 956.2519951.793948.80699954.959946.5241
9963.741940.72299973.232935.51479975.689934.52559987.636930.49019991.505930.3715
9999.584930.414510009.78931.054110011.53931.489710023.48939.973410028.05942.6966
10035.43945.174710071.27956.522210083.22 959.38910095.17960.870310113.01961.8716
#Mann= 3 , 0 , 0
9829.873    0.12       09829.873    0.12       010113.01    0.12       0
#XS Ineff= 2 , 0
       0                               0
Bank Sta=9829.873,10113.01
Exp/Cntr=0.3,0.1

Type RM Length L Ch R = 1 ,7652.282,148.938300,148.938300,148.938300
XS GIS Cut Line= 3
521200.091816187825374.098749951 521400.61264953825473.057083294
521504.779316187825463.942499965
#Sta/Elev= 30
9832.788974.70229860.564 970.0249871.715966.55319882.867 964.5449894.018 962.187
 9905.17960.50769916.321959.1751 9925.21959.40569927.473959.30339938.624 958.073
9947.806954.02489949.776952.88329960.927943.87919970.402938.04739972.078 937.355
 9983.23  934.369992.999928.69619994.381928.028210005.53928.2329 10015.6931.3825
10027.84936.538110038.99937.748310050.14940.023110070.84946.129810080.88949.2799
10100.95954.163910110.99955.685610131.07957.452210141.11958.114310160.96958.5963
#Mann= 3 , 0 , 0
9832.788    0.12       09832.788    0.12       010160.96    0.12       0
#XS Ineff= 2 , 0
       0                               0
Bank Sta=9832.788,10160.96
Exp/Cntr=0.3,0.1

Type RM Length L Ch R = 1 ,7503.344,146.072800,146.072800,146.072800
XS GIS Cut Line= 4
521128.477232873825514.723749951521243.060566187825577.223749951
 521334.20639953825581.129999965 521463.11264953825641.025833294
#Sta/Elev= 30
9825.561969.90769832.991968.71129855.773963.63389867.164961.33119878.555960.1549
9901.336958.31619912.727957.15559930.554955.9807  9946.9955.27339958.023953.4107
9968.032946.84319978.041935.6625 9988.05929.37539998.059928.589310008.07928.5453
10018.08933.402110028.09936.552310048.19940.928710059.21943.714410070.24945.7619
10081.27947.014210092.29948.804710103.32950.037210114.35951.015410127.69 951.692
 10136.4952.394410147.43953.805510158.45955.976210169.48 957.87610189.45960.3097
#Mann= 3 , 0 , 0
9825.561    0.04       09825.561    0.04       010189.45    0.04       0
#XS Ineff= 2 , 0
       0                               0
Bank Sta=9825.561,10189.45
Exp/Cntr=0.3,0.1

Type RM Length L Ch R = 1 ,7357.271,94.902100,94.902100,94.902100
XS GIS Cut Line= 2
 521166.23764953825659.254999965521325.091816187825773.838333294
#Sta/Elev= 29
 9919.74954.6279 9929.56959.13899930.544959.38729942.874959.08159946.654958.6739
9955.204956.49349963.748953.28759967.534950.78859979.864938.50439980.842937.2883
9992.194926.65439997.935 926.23810004.52926.537810015.03  929.0110016.85929.6076
10029.18935.689210032.12937.327710041.51943.159910049.22947.608310053.84950.2746
10066.17957.245810066.31957.3065 10078.5 962.257 10083.4963.887610090.83966.2683
 10100.5969.542110103.16 970.31910115.49973.818310115.61973.8523
#Mann= 3 , 0 , 0
 9919.74    0.04       0 9919.74    0.04       010115.61    0.04       0
#XS Ineff= 2 , 0
       0                               0
Bank Sta=9919.74,10115.61
Exp/Cntr=0.3,0.1

Type RM Length L Ch R = 1 ,7262.369,111.485400,111.485400,111.485400
XS GIS Cut Line= 2
 521060.76889956825759.515416607521276.914732873825797.275833294
#Sta/Elev= 28
 9885.28980.77969889.576979.65819899.727976.33089909.879970.1321 9917.15964.9271
 9920.03962.85989930.181954.52699940.333946.87699950.484938.69349960.636933.2303
9970.787927.16759975.259 925.7969980.939 924.262 9991.09923.622710001.24923.3657
10011.39925.294210021.54931.1947 10031.7938.532510033.37940.125210041.85948.5635
   10052956.680410062.15963.0682 10072.3968.125610082.45 972.55710091.48975.4658
 10092.6975.782710102.76977.7897 10104.7978.1832
#Mann= 3 , 0 , 0
 9885.28    0.12       0 9885.28    0.12       0 10104.7    0.12       0
#XS Ineff= 2 , 0
       0                               0
Bank Sta=9885.28,10104.7
Exp/Cntr=0.3,0.1

Type RM Length L Ch R = 1 ,7150.883,126.017000,126.017000,126.017000
XS GIS Cut Line= 2
 521092.01889956825907.952916607521296.445982903825867.588333294
#Sta/Elev= 27
9901.631982.7682 9904.67982.04829914.863 979.2349916.875978.74729925.056976.6624
9935.249972.59369945.442 961.9879955.635 949.5419965.828939.38929968.498937.1515
9976.021931.07189986.214921.74489996.407917.7245 10006.6 919.62310016.79926.6904
10020.12928.979310026.99933.637510037.18 942.37810047.37949.795710057.57958.6909
10067.76968.396710071.74969.890210077.95972.139310088.14976.725410098.34978.7021
10108.53 979.471   10110979.5311
#Mann= 3 , 0 , 0
9901.631    0.04       09901.631    0.04       0   10110    0.04       0
#XS Ineff= 2 , 0
       0                               0
Bank Sta=9901.631,10110
Exp/Cntr=0.3,0.1