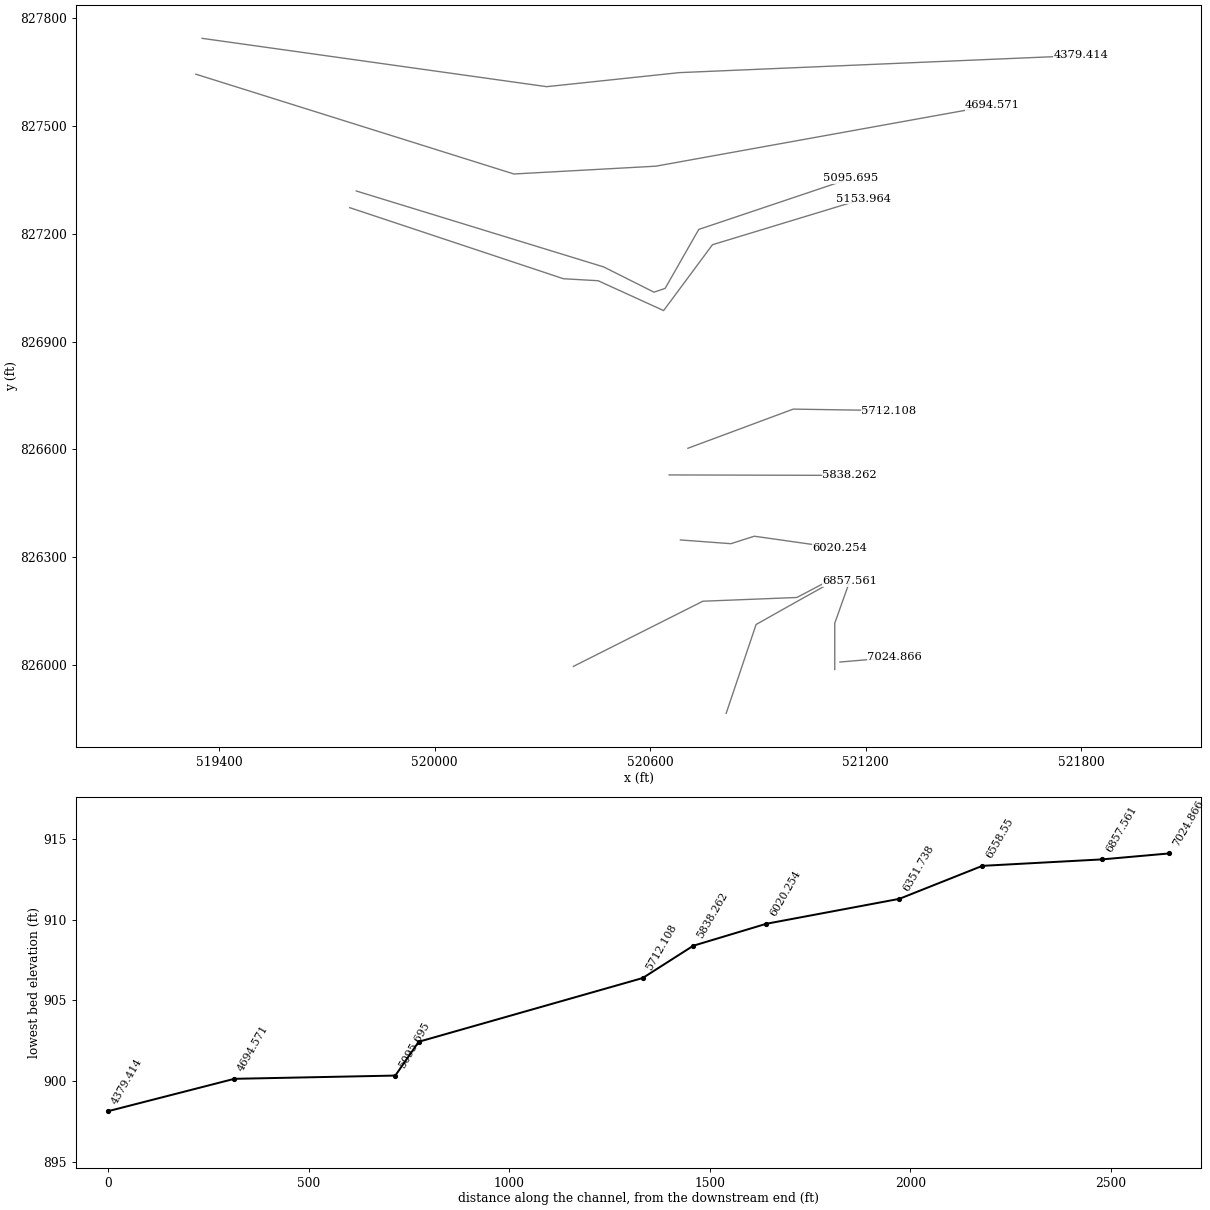
HEC-RAS study 7919_ras.prj: 7919

--- 7919_ras.g01 (geometry) --- (continued)

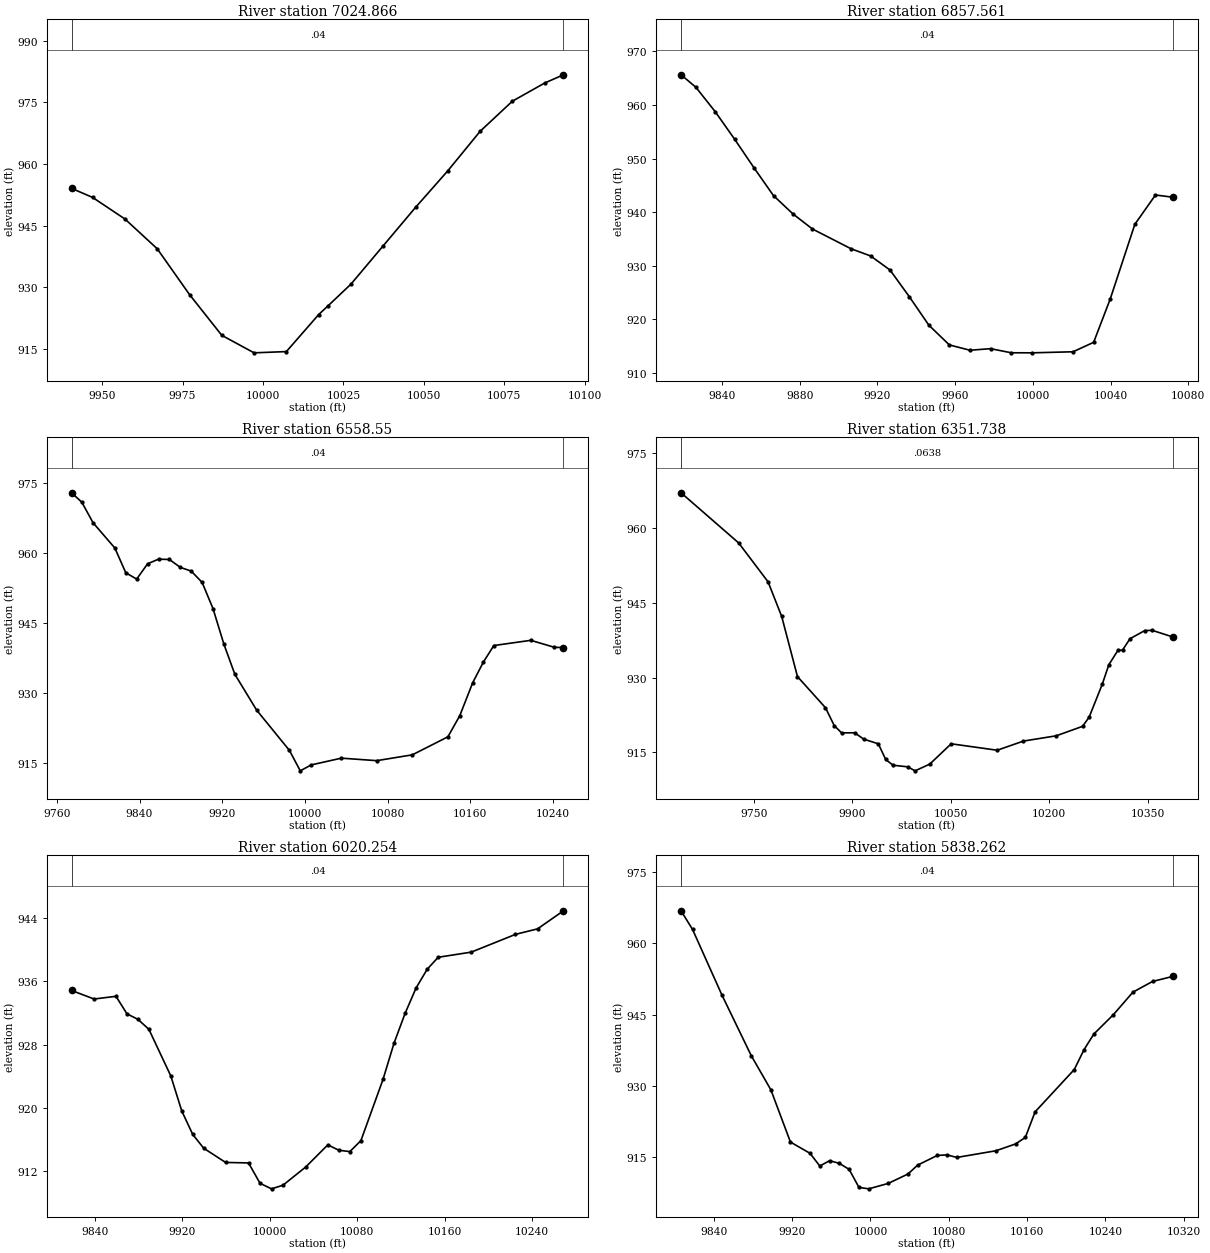
Type RM Length L Ch R = 1 ,7024.866,167.305100,167.305100,167.305100
XS GIS Cut Line= 2
521128.477232873826008.213333294521280.820982903826021.234166622
#Sta/Elev= 18
9940.494 954.087 9947.04951.87529957.077946.63569967.113939.4021 9977.15 928.261
9987.186918.34499997.223  914.0910007.26914.3968 10017.3923.397910020.19925.5074
10027.33930.794310037.37940.133810047.41949.460610057.44958.356310067.48967.9577
10077.51975.285410087.55979.700910093.39 981.705
#Mann= 3 , 0 , 0
9940.494    0.04       09940.494    0.04       010093.39    0.04       0
#XS Ineff= 2 , 0
       0                               0
Bank Sta=9940.494,10093.39
Exp/Cntr=0.3,0.1

Type RM Length L Ch R = 1 ,6857.561,299.011700,299.011700,299.011700
XS GIS Cut Line= 3
521114.154316187825987.379999951521114.154316187826116.286249965
521155.820982873826233.473749965
#Sta/Elev= 24
9818.861965.64549826.481963.32219836.481958.74579846.481953.59869856.481948.2464
9866.481943.07269876.481939.66519886.481936.85449906.481933.14189916.481931.8156
9926.481929.18119936.481924.16389946.481918.87799957.015   915.29967.628914.2039
9978.242914.50059988.855913.73529999.468913.721210020.69913.919110031.31915.6859
10039.84923.763310052.53937.724910063.15943.198210072.14942.7776
#Mann= 3 , 0 , 0
9818.861    0.04       09818.861    0.04       010072.14    0.04       0
#XS Ineff= 2 , 0
       0                               0
Bank Sta=9818.861,10072.14
Exp/Cntr=0.3,0.1

Type RM Length L Ch R = 1 , 6558.55,206.812000,206.812000,206.812000
XS GIS Cut Line= 4
 520811.82358703825865.289432824520895.156920373826112.685266167
521020.156920373826182.997766167521082.656920403826217.719988376
#Sta/Elev= 30
9774.272972.89889784.223970.86699795.071966.47139816.175961.05179826.727955.7534
9837.279954.41069847.832 957.6839858.384958.67149868.936958.60659879.488956.9175
 9890.04956.11559900.592953.69459911.144948.06879921.696940.43539932.248934.0139
9953.352926.32619985.008917.71879995.561913.320910006.11914.588310035.33916.0377
10069.57915.501910103.99  916.7510138.41920.612110149.88925.127510162.43932.2106
10172.83936.665710182.87940.1689 10218.6941.284210241.48939.787710250.24939.7323
#Mann= 3 , 0 , 0
9774.272    0.04       09774.272    0.04       010250.24    0.04       0
#XS Ineff= 2 , 0
       0                               0
Bank Sta=9774.272,10250.24
Exp/Cntr=0.3,0.1

Type RM Length L Ch R = 1 ,6351.738,331.483700,331.483700,331.483700
XS GIS Cut Line= 4
520386.574039131825996.067149952520746.966816187826177.484166637
521008.685566187826187.900833279521082.904316187826226.963333279
#Sta/Elev= 30
 9639.34967.10269727.142957.03229771.924949.2194 9792.65 942.2829816.706930.1975
9859.371 923.9519872.684920.3659 9883.88918.90339903.852918.92119917.466917.6489
9939.857916.70919951.053913.56879962.248912.40699984.639912.08579995.835911.2811
10018.23912.634310050.86916.709310120.91915.416710160.95917.257210210.99918.3184
10251.02920.221610261.02922.071610281.04928.691610291.05932.611110304.74935.4427
10311.88935.527810323.18937.801110345.78939.442810357.08939.484310388.62938.1466
#Mann= 3 , 0 , 0
 9639.34  0.0638       0 9639.34  0.0638       010388.62  0.0638       0
#XS Ineff= 2 , 0
       0                               0
Bank Sta=9639.34,10388.62
Exp/Cntr=0.3,0.1

Type RM Length L Ch R = 1 ,6020.254,181.991600,181.991600,181.991600
XS GIS Cut Line= 4
520684.466816187826348.057083294520825.091816217826337.640416622
520890.195982873826358.473749965521128.477232873826324.619583294
#Sta/Elev= 30
9818.759934.85529839.348933.77659859.403934.11799869.431931.90099879.458931.2027
9889.485929.9418 9909.54924.03779919.568919.59989929.595916.63249939.622914.8853
9959.677913.08229980.672913.02079991.171910.442810001.67909.740110012.17910.1985
10032.98912.506210053.18915.307110063.28914.625510073.38914.455310083.48915.8472
10103.68923.589410113.78928.187910123.91931.965610133.98935.183210144.08937.5414
10154.18939.061410184.48939.713510224.89941.961110245.09942.6589 10268.8 944.948
#Mann= 3 , 0 , 0
9818.759    0.04       09818.759    0.04       0 10268.8    0.04       0
#XS Ineff= 2 , 0
       0                               0
Bank Sta=9818.759,10268.8
Exp/Cntr=0.3,0.1

Type RM Length L Ch R = 1 ,5838.262,126.154100,126.154100,126.154100
XS GIS Cut Line= 2
520653.216816187826529.046666607521155.820982873826527.744583294
#Sta/Elev= 30
9806.448 966.7939818.231962.86719848.232 949.0939878.232936.34049898.232929.1887
9918.232918.20769938.232915.84749948.232913.17439958.232914.29729968.232913.7326
9978.232912.46549988.232 908.6879998.232908.382510018.23909.526110038.23911.4883
10048.23913.368110068.23915.394310078.23 915.51310088.23914.978310128.23916.3834
10148.23917.809910158.23 919.17910168.23924.560610208.23933.441710218.23937.6287
10228.23940.901710248.23944.975410268.23949.709410288.23951.947510309.05953.0168
#Mann= 3 , 0 , 0
9806.448    0.04       09806.448    0.04       010309.05    0.04       0
#XS Ineff= 2 , 0
       0                               0
Bank Sta=9806.448,10309.05
Exp/Cntr=0.3,0.1

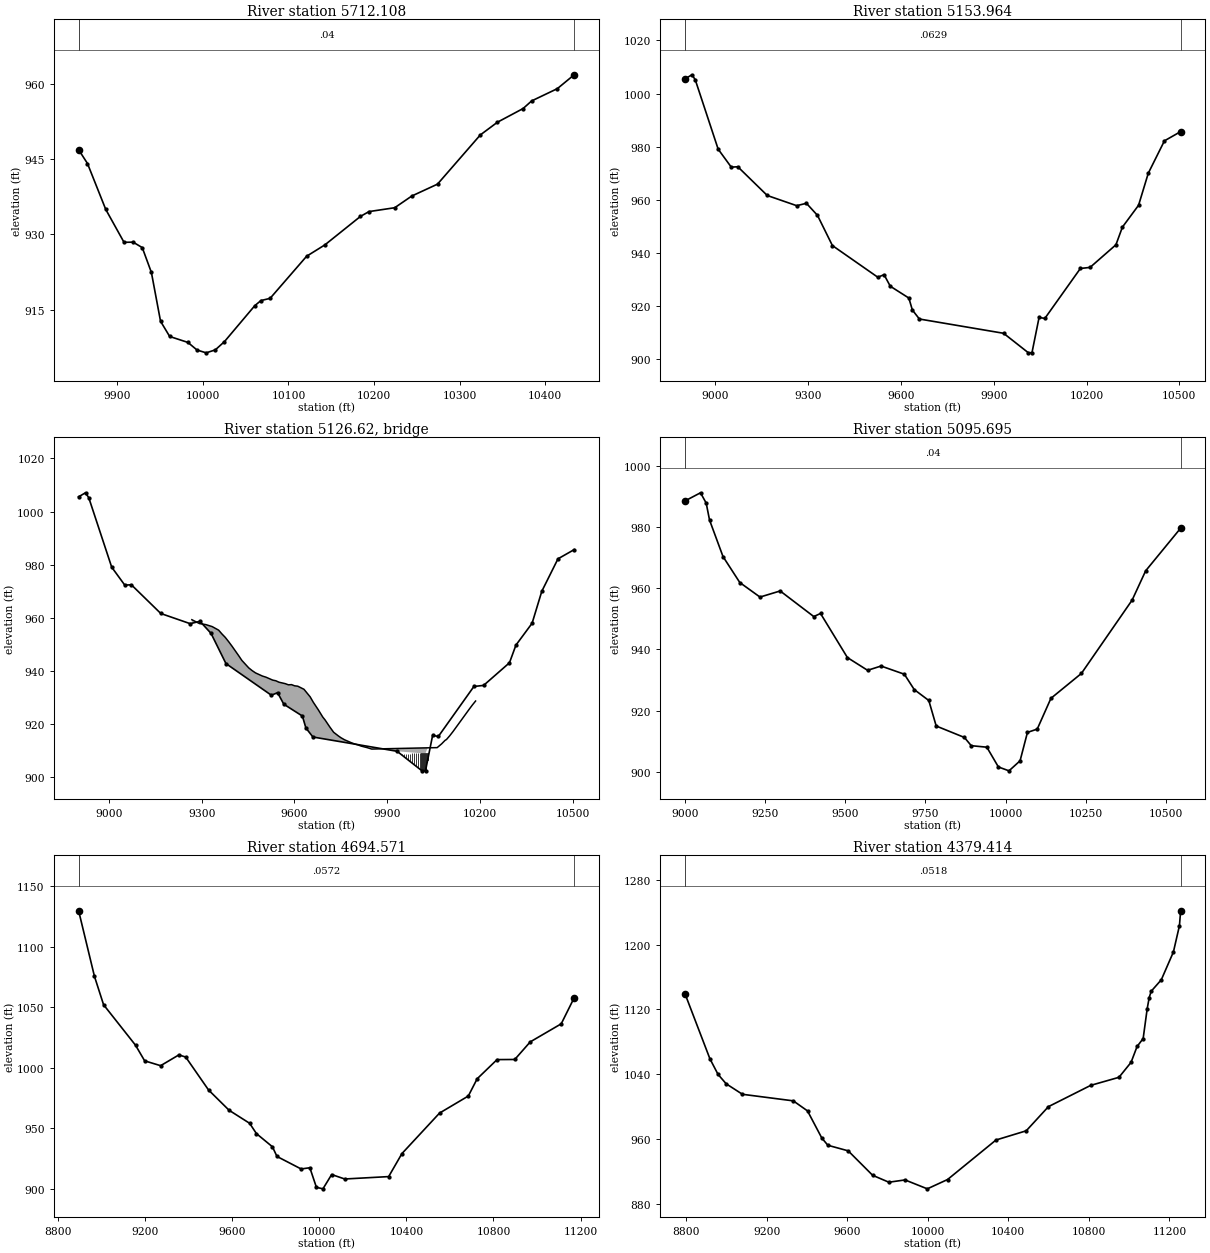
Type RM Length L Ch R = 1 ,5712.108,558.144200,558.144200,558.144200
XS GIS Cut Line= 3
 520705.30014953826603.265416637520998.496864796 826712.26382035
521264.669573694826708.147747532
#Sta/Elev= 30
9854.791946.8674 9865.14944.11779886.477 934.9699907.814928.41629918.483928.4455
9929.152927.3567 9939.82922.40319950.489912.68899961.158909.64989982.495908.4612
9993.164906.943110003.83906.3861 10014.5906.977510025.17908.620710060.65915.7936
10067.84916.807510078.51917.244610121.19925.638810142.53927.9044 10184.1933.5821
 10194.1934.5399 10224.1 935.30610244.11937.645810274.11940.008510324.12949.8129
10344.12952.348510374.12955.076910384.12 956.59510414.13959.0403 10433.8961.8053
#Mann= 3 , 0 , 0
9854.791    0.04       09854.791    0.04       0 10433.8    0.04       0
#XS Ineff= 2 , 0
       0                               0
Bank Sta=9854.791,10433.8
Exp/Cntr=0.3,0.1

Type RM Length L Ch R = 1 ,5153.964,58.269100,58.269100,58.269100
XS GIS Cut Line= 6
519764.005882919   827273.009011520358.929892987827075.187928393
520455.398027658827069.649088144  520637.7181862826986.566484183
520773.706580311827169.864809111521195.103723943827297.922825664
#Sta/Elev= 30
8902.4111005.5488924.6271007.0518935.2091005.1899009.284979.06959051.613972.3079
9072.777 972.4499168.017961.63859263.098957.80599294.593958.70449330.345 954.159
9378.538942.80259525.299930.89099545.515931.84679565.548927.50959625.647923.0562
9636.949918.5697 9659.66915.17119931.845909.800310012.19902.446410023.67902.5433
10046.62915.802110065.04915.3675   10180934.180910211.36934.589210294.97943.0977
10315.87949.741310368.13957.971510399.49 970.00210451.74982.202910504.11985.6671
#Mann= 3 , 0 , 0
8902.411  0.0629       08902.411  0.0629       010504.11  0.0629       0
#XS Ineff= 2 , 0
       0                               0
Bank Sta=8902.411,10504.11
Exp/Cntr=0.3,0.1

Type RM Length L Ch R = 3 , 5126.62,,,
BEGIN DESCRIPTION:
END DESCRIPTION:
Bridge Culvert--1,0,-1,-1, 0
Deck Dist Width WeirC Skew NumUp NumDn MinLoCord MaxHiCord MaxSubmerge Is_Ogee
19.134550,20.000000,2.6,0, 54, 54, , , 0.95, 0, 0,0,,
 9268.41 9293.08 9313.55 9334.03 9354.92 9365.64 9376.37 9387.10 9397.83 9419.29
 9430.01 9452.12 9463.22 9474.32 9496.51 9507.61 9529.68 9539.82 9549.95 9570.22
 9580.35 9590.49 9600.62 9610.67 9630.73 9650.80 9660.83 9677.45 9691.73 9698.73
 9714.71 9726.62 9742.26 9750.44 9761.72 9783.54 9794.45 9805.14 9815.48 9836.17
 9849.63 9878.80 9878.8010048.8010048.8010061.3410075.8210086.9610091.3710101.87
10112.3710164.8910175.4010185.45
  959.30  957.84  957.46  956.71  955.37  953.94  952.65  951.07  949.39  945.84
  943.99  941.19  940.15  939.28  938.10  937.70  936.58  936.33  935.79  935.25
  934.81  934.88  934.43  934.29  933.13  930.28  928.26  925.34  922.64  921.63
  918.87  916.96  915.55  914.89  914.14  913.03  912.56  912.22  911.76  911.14
  910.64  910.72  910.72  911.15  911.15  911.18  912.61  913.93  914.23  915.64
  917.21  925.63  927.26  928.71
  -40.70  -42.16  -42.54  -43.29  -44.63  -46.06  -47.35  -48.93  -50.61  -54.16
  -56.01  -58.81  -59.85  -60.72  -61.90  -62.30  -63.42  -63.67  -64.21  -64.75
  -65.19  -65.12  -65.57  -65.71  -66.87  -69.72  -71.74  -74.66  -77.36  -78.37
  -81.13  -83.04  -84.45  -85.11  -85.86  -86.97  -87.44  -87.78  -88.24  -88.86
  -89.36  -89.28  908.72  909.15  -88.85  -88.82  -87.39  -86.07  -85.77  -84.36
  -82.79  -74.37  -72.74  -71.29
 9268.41 9293.08 9313.55 9334.03 9354.92 9365.64 9376.37 9387.10 9397.83 9419.29
 9430.01 9452.12 9463.22 9474.32 9496.51 9507.61 9529.68 9539.82 9549.95 9570.22
 9580.35 9590.49 9600.62 9610.67 9630.73 9650.80 9660.83 9677.45 9691.73 9698.73
 9714.71 9726.62 9742.26 9750.44 9761.72 9783.54 9794.45 9805.14 9815.48 9836.17
 9849.63 9899.59 9899.5910061.3410069.5910069.5910075.8210086.9610091.3710101.87
10122.8810164.8910175.4010185.45
  959.30  957.84  957.46  956.71  955.37  953.94  952.65  951.07  949.39  945.84
  943.99  941.19  940.15  939.28  938.10  937.70  936.58  936.33  935.79  935.25
  934.81  934.88  934.43  934.29  933.13  930.28  928.26  925.34  922.64  921.63
  918.87  916.96  915.55  914.89  914.14  913.03  912.56  912.22  911.76  911.14
  910.64  910.77  910.77  911.18  911.97  911.97  912.61  913.93  914.23  915.64
  918.86  925.63  927.26  928.71
  -40.70  -42.16  -42.54  -43.29  -44.63  -46.06  -47.35  -48.93  -50.61  -54.16
  -56.01  -58.81  -59.85  -60.72  -61.90  -62.30  -63.42  -63.67  -64.21  -64.75
  -65.19  -65.12  -65.57  -65.71  -66.87  -69.72  -71.74  -74.66  -77.36  -78.37
  -81.13  -83.04  -84.45  -85.11  -85.86  -86.97  -87.44  -87.78  -88.24  -88.86
  -89.36  -89.23  908.77  909.18  909.97  -88.03  -87.39  -86.07  -85.77  -84.36
  -81.14  -74.37  -72.74  -71.29
Pier Skew, UpSta & Num, DnSta & Num=  ,9884.17, 2 ,9904.96, 2 , 0 , 0 , 0 ,,
    2.00    2.00
  -89.27  910.73
    2.00    2.00
  -89.22  910.78
Pier Skew, UpSta & Num, DnSta & Num=  ,9890.54, 2 ,9911.33, 2 , 0 , 0 , 0 ,,
    2.00    2.00
  -89.25  910.75
    2.00    2.00
  -89.20  910.80
Pier Skew, UpSta & Num, DnSta & Num=  ,9896.91, 2 ,9917.70, 2 , 0 , 0 , 0 ,,
    2.00    2.00
  -89.24  910.76
    2.00    2.00
  -89.18  910.82
Pier Skew, UpSta & Num, DnSta & Num=  ,9903.28, 2 ,9924.07, 2 , 0 , 0 , 0 ,,
    2.00    2.00
  -89.22  910.78
    2.00    2.00
  -89.17  910.83
Pier Skew, UpSta & Num, DnSta & Num=  ,9909.65, 2 ,9930.44, 2 , 0 , 0 , 0 ,,
    2.00    2.00
  -89.20  910.80
    2.00    2.00
  -89.15  910.85
Pier Skew, UpSta & Num, DnSta & Num=  ,9916.02, 2 ,9936.81, 2 , 0 , 0 , 0 ,,
    2.00    2.00
  -89.19  910.81
    2.00    2.00
  -89.14  910.86
Pier Skew, UpSta & Num, DnSta & Num=  ,9922.39, 2 ,9943.18, 2 , 0 , 0 , 0 ,,
    2.00    2.00
  -89.17  910.83
    2.00    2.00
  -89.12  910.88
Pier Skew, UpSta & Num, DnSta & Num=  ,9928.76, 2 ,9949.55, 2 , 0 , 0 , 0 ,,
    2.00    2.00
  -89.16  910.84
    2.00    2.00
  -89.10  910.90
Pier Skew, UpSta & Num, DnSta & Num=  ,9935.13, 2 ,9955.92, 2 , 0 , 0 , 0 ,,
    2.00    2.00
  -89.14  910.86
    2.00    2.00
  -89.09  910.91
Pier Skew, UpSta & Num, DnSta & Num=  ,9941.50, 2 ,9962.29, 2 , 0 , 0 , 0 ,,
    2.00    2.00
  -89.12  910.88
    2.00    2.00
  -89.07  910.93
Pier Skew, UpSta & Num, DnSta & Num=  ,9947.87, 2 ,9968.66, 2 , 0 , 0 , 0 ,,
    2.00    2.00
  -89.11  910.89
    2.00    2.00
  -89.06  910.94
Pier Skew, UpSta & Num, DnSta & Num=  ,9954.24, 2 ,9975.03, 2 , 0 , 0 , 0 ,,
    2.00    2.00
  -89.09  910.91
    2.00    2.00
  -89.04  910.96
Pier Skew, UpSta & Num, DnSta & Num=  ,9960.61, 2 ,9981.40, 2 , 0 , 0 , 0 ,,
    2.00    2.00
  -89.08  910.92
    2.00    2.00
  -89.02  910.98
Pier Skew, UpSta & Num, DnSta & Num=  ,9966.98, 2 ,9987.77, 2 , 0 , 0 , 0 ,,
    2.00    2.00
  -89.06  910.94
    2.00    2.00
  -89.01  910.99
Pier Skew, UpSta & Num, DnSta & Num=  ,9973.35, 2 ,9994.14, 2 , 0 , 0 , 0 ,,
    2.00    2.00
  -89.04  910.96
    2.00    2.00
  -88.99  911.01
Pier Skew, UpSta & Num, DnSta & Num=  ,9979.72, 2 ,10000.51, 2 , 0 , 0 , 0 ,,
    2.00    2.00
  -89.03  910.97
    2.00    2.00
  -88.98  911.02
Pier Skew, UpSta & Num, DnSta & Num=  ,9986.09, 2 ,10006.88, 2 , 0 , 0 , 0 ,,
    2.00    2.00
  -89.01  910.99
    2.00    2.00
  -88.96  911.04
Pier Skew, UpSta & Num, DnSta & Num=  ,9992.46, 2 ,10013.25, 2 , 0 , 0 , 0 ,,
    2.00    2.00
  -89.00  911.00
    2.00    2.00
  -88.94  911.06
Pier Skew, UpSta & Num, DnSta & Num=  ,9998.83, 2 ,10019.62, 2 , 0 , 0 , 0 ,,
    2.00    2.00
  -88.98  911.02
    2.00    2.00
  -88.93  911.07
Pier Skew, UpSta & Num, DnSta & Num=  ,10005.20, 2 ,10025.99, 2 , 0 , 0 , 0 ,,
    2.00    2.00
  -88.96  911.04
    2.00    2.00
  -88.91  911.09
Pier Skew, UpSta & Num, DnSta & Num=  ,10011.57, 2 ,10032.37, 2 , 0 , 0 , 0 ,,
    2.00    2.00
  -88.95  911.05
    2.00    2.00
  -88.89  911.11
Pier Skew, UpSta & Num, DnSta & Num=  ,10017.94, 2 ,10038.74, 2 , 0 , 0 , 0 ,,
    2.00    2.00
  -88.93  911.07
    2.00    2.00
  -88.88  911.12
Pier Skew, UpSta & Num, DnSta & Num=  ,10024.31, 2 ,10045.11, 2 , 0 , 0 , 0 ,,
    2.00    2.00
  -88.92  911.08
    2.00    2.00
  -88.86  911.14
Pier Skew, UpSta & Num, DnSta & Num=  ,10030.68, 2 ,10051.48, 2 , 0 , 0 , 0 ,,
    2.00    2.00
  -88.90  911.10
    2.00    2.00
  -88.85  911.15
Pier Skew, UpSta & Num, DnSta & Num=  ,10037.05, 2 ,10057.85, 2 , 0 , 0 , 0 ,,
    2.00    2.00
  -88.88  911.12
    2.00    2.00
  -88.83  911.17
Pier Skew, UpSta & Num, DnSta & Num=  ,10043.43, 2 ,10064.22, 2 , 0 , 0 , 0 ,,
    2.00    2.00
  -88.87  911.13
    2.00    2.00
  -88.54  911.46
BR Coef=-1 , 0 , 0 ,, 0 ,,,0.8,0,1,0,
WSPro=,,,, 1 ,,,, 0 ,,,, 0 ,,,,-1 ,-1 ,-1 , 0 , 0 , 0 , 0 , 0
BC Design=,, 0 ,, 0 ,,,,,,

Type RM Length L Ch R = 1 ,5095.695,401.124100,401.124100,401.124100
XS GIS Cut Line= 6
519782.282311218 827319.44605841520470.897188008827108.058172122
520611.088160217827037.745672122520641.980095983827048.382394657
520735.512135863 827212.39953132521158.385038443827354.522346396
#Sta/Elev= 30
9000.622988.50729048.662991.15379066.383987.78699076.869982.2388 9118.81970.3293
9171.236961.84279234.148 957.099 9297.06959.09479401.913950.73049422.884951.7435
9506.766937.33979569.678933.18369611.619934.57959684.282931.90639715.086926.8975
9760.507923.32869783.594914.99689871.516911.25829892.896908.56969941.496908.0791
9977.511901.624910010.57900.3574 10045.1903.636710068.12912.910710098.63913.9875
10141.32924.032410236.27932.153810394.52956.110910436.72965.669410545.78979.5958
#Mann= 3 , 0 , 0
9000.622    0.04       09000.622    0.04       010545.78    0.04       0
#XS Ineff= 2 , 0
       0                               0
Bank Sta=9000.622,10545.78
Exp/Cntr=0.3,0.1

Type RM Length L Ch R = 1 ,4694.571,315.157000,315.157000,315.157000
XS GIS Cut Line= 4
519335.659736544827644.564349204 520221.07640323827366.786571428
520616.041680962827388.487960339521553.541680962827557.758793667
#Sta/Elev= 30
8894.6381129.4828967.3111075.4099009.2331051.9829155.9611018.6059197.8841005.719
9271.2481001.7269355.0921010.6219386.5341008.839 9491.34 981.6929585.665964.9787
 9679.99954.22289711.432945.69319784.796934.84159805.757926.86129916.671916.5421
9956.731917.55379986.777901.424610016.82 900.15610056.88911.951410116.97 908.275
10318.73910.2535 10379.7 929.23610552.44962.634710684.55976.696510725.19990.9233
10816.651006.74110897.941006.84610969.071021.35811111.341036.25111170.831057.727
#Mann= 3 , 0 , 0
8894.638  0.0572       08894.638  0.0572       011170.83  0.0572       0
#XS Ineff= 2 , 0
       0                               0
Bank Sta=8894.638,11170.83
Exp/Cntr=0.3,0.1

Type RM Length L Ch R = 1 ,4379.414,390.143600,390.143600,390.143600
XS GIS Cut Line= 4
519353.020847648827744.390738115520312.222236544827609.842126995
520681.145847648827648.904626995521800.937514335827696.647682533
#Sta/Elev= 30
8795.3211139.1588918.4941059.0458958.8861039.7298999.2771028.0819080.0611015.104
9332.5081006.9879403.193994.53369473.879961.09769504.172952.03839605.151945.1511
9726.326914.9215 9806.93906.34569887.377909.17039997.992898.152310098.55909.6868
10338.94958.550410489.07969.940710599.17999.800610809.371026.15910949.491036.104
11009.551054.61511039.571074.319 11069.61084.01811089.621120.90811099.631134.738
11109.641142.60811159.681156.73511219.741191.11111249.76 1223.6611255.711242.105
#Mann= 3 , 0 , 0
8795.321  0.0518       08795.321  0.0518       011255.71  0.0518       0
#XS Ineff= 2 , 0
       0                               0
Bank Sta=8795.321,11255.71
Exp/Cntr=0.3,0.1