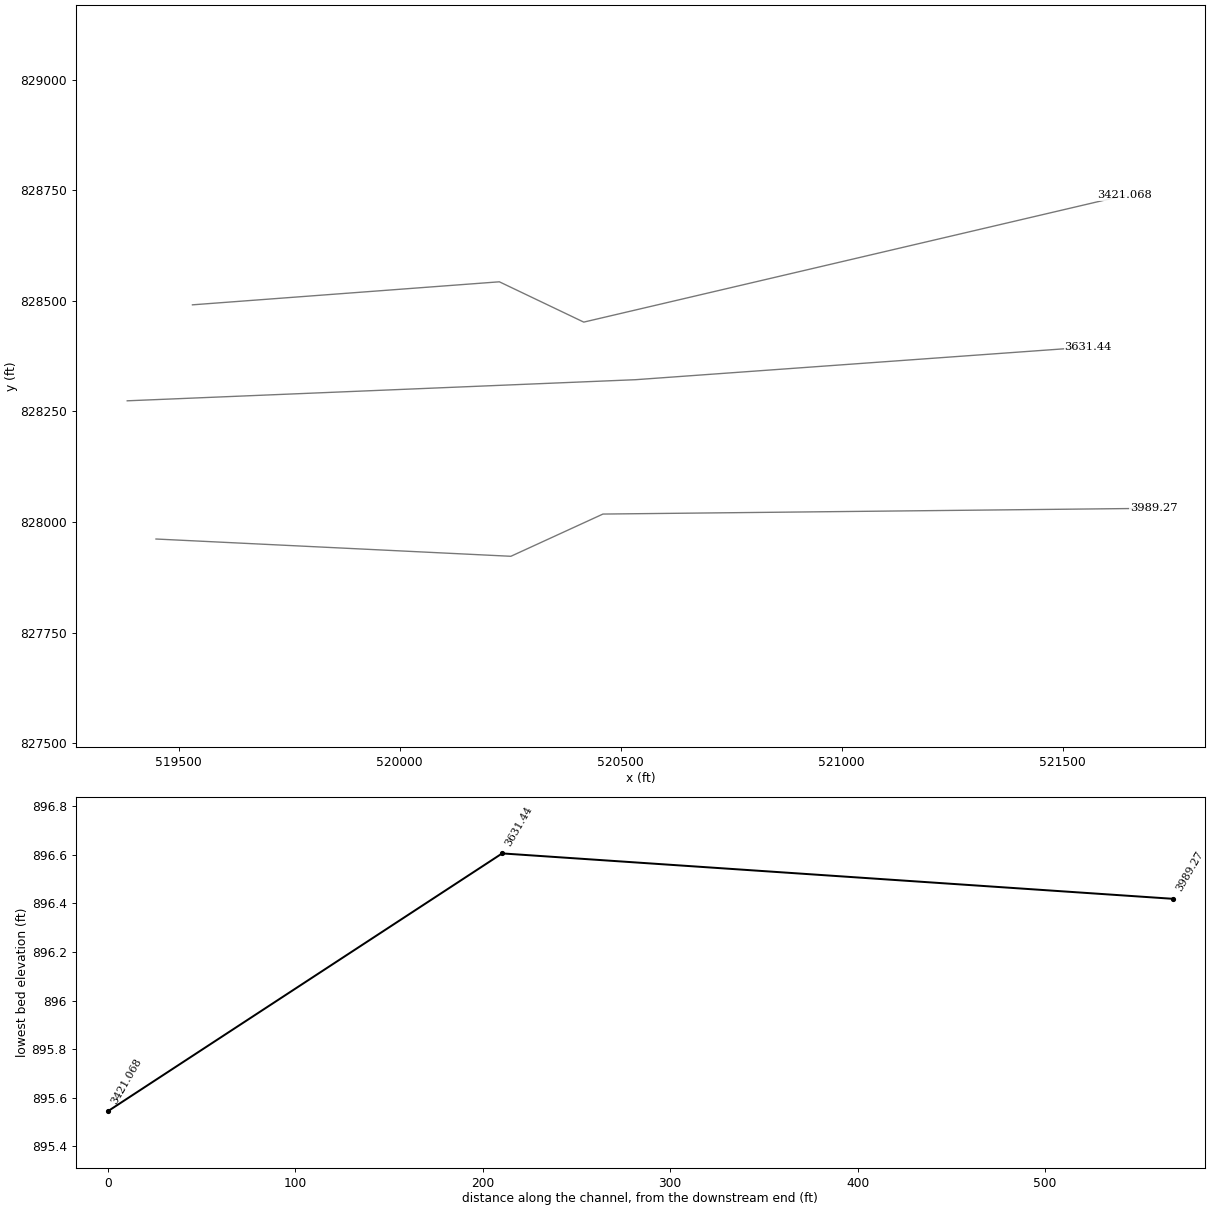
HEC-RAS study 7919_ras.prj: 7919

--- 7919_ras.g01 (geometry) --- (continued)

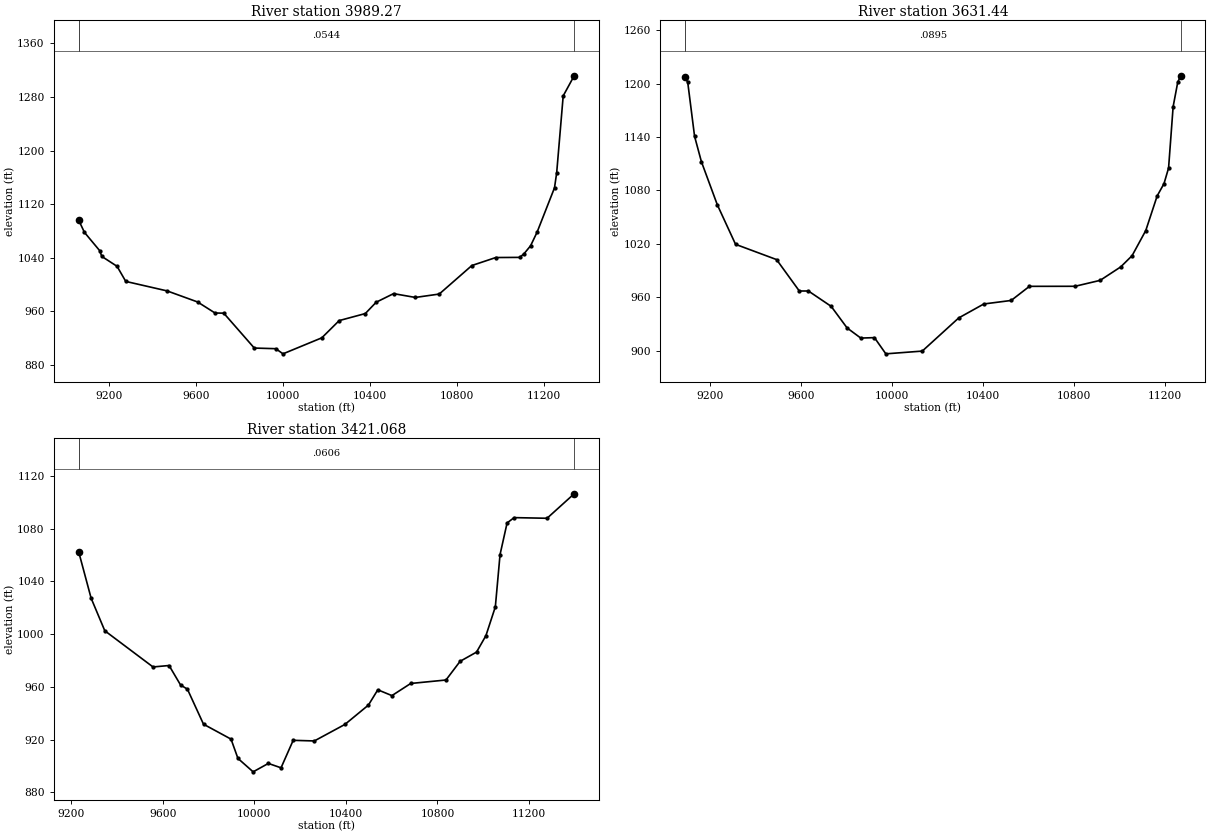
Type RM Length L Ch R = 1 , 3989.27,357.830200,357.830200,357.830200
XS GIS Cut Line= 4
519448.506958753 827961.40462698520251.458347678 827922.34212698
520459.791680962  828017.8282381521705.451403201828030.849071443
#Sta/Elev= 30
9059.1021096.2039085.626 1077.869155.7091050.5649165.7211041.8639235.804 1027.09
9275.8511004.5529466.076990.36919606.241973.84859686.336957.38049726.383957.1652
9866.899905.05139965.902904.10389998.903896.418610177.39920.331510257.39946.0721
 10377.4 956.562 10427.4973.476610507.41986.318110607.41980.621210717.42985.6867
10867.431028.27810977.431040.20911087.441040.43211107.441045.94411137.441057.744
11167.441078.11611247.45 1144.3211257.451166.71511287.451281.594 11337.91311.582
#Mann= 3 , 0 , 0
9059.102  0.0544       09059.102  0.0544       0 11337.9  0.0544       0
#XS Ineff= 2 , 0
       0                               0
Bank Sta=9059.102,11337.9
Exp/Cntr=0.3,0.1

Type RM Length L Ch R = 1 , 3631.44,210.371400,210.371400,210.371400
XS GIS Cut Line= 3
519383.402792126 828273.90462698520533.576403201828321.647682548
521557.881958753828395.432404757
#Sta/Elev= 30
9090.8511206.9739102.4591201.3739132.4851140.816 9162.511112.3249232.5711063.868
 9312.64 1019.559492.7951002.4329592.881967.15519632.915967.15339733.001949.8909
9803.061925.63819863.113 914.3039923.165914.79429973.208896.605410133.35899.6896
10293.57936.916210403.86952.579910524.17956.532210604.38972.385310804.89972.4394
10915.18979.090811005.41 994.16511055.541006.784 11115.71035.01611165.831073.898
 11195.91087.69211215.961105.22711236.011174.12111256.061201.27411268.981208.758
#Mann= 3 , 0 , 0
9090.851  0.0895       09090.851  0.0895       011268.98  0.0895       0
#XS Ineff= 2 , 0
       0                               0
Bank Sta=9090.851,11268.98
Exp/Cntr=0.3,0.1

Type RM Length L Ch R = 1 ,3421.068,0.000000,0.000000,0.000000
XS GIS Cut Line= 4
519530.972236544828490.918515876520225.416680962828543.001849219
520416.388903201828451.856015876521640.347236544828738.314349204
#Sta/Elev= 30
9232.4451062.5289287.017  1027.29346.7931002.5049557.383975.06789627.579976.1601
 9677.72961.41729707.804958.2124    9778931.66939898.337920.33979928.422905.7331
9994.861895.544410061.34901.919710116.75 898.59410169.83919.438910262.26918.9639
10395.78931.486510498.48946.145610539.56957.748210601.18953.343810683.34962.5468
 10837.4965.177110899.02  979.3310970.91986.331611011.99998.836111053.07 1020.67
11073.611060.25911104.421084.26611135.231088.29511279.021087.80411397.481106.374
#Mann= 3 , 0 , 0
9232.445  0.0606       09232.445  0.0606       011397.48  0.0606       0
#XS Ineff= 2 , 0
       0                               0
Bank Sta=9232.445,11397.48
Exp/Cntr=0.3,0.1